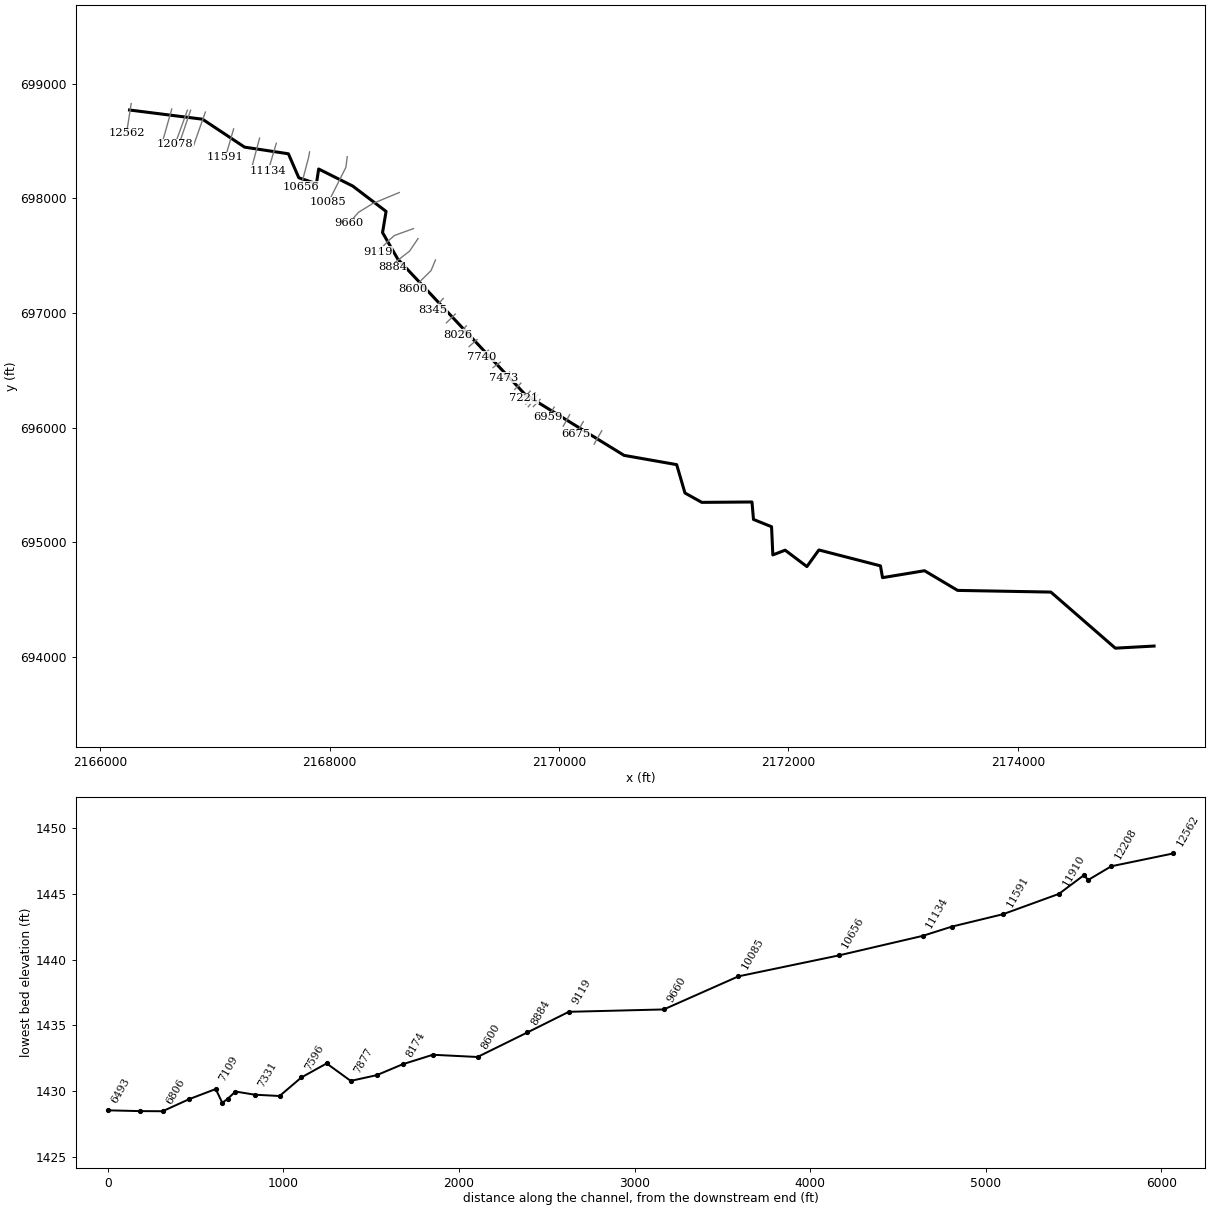
--- BULLRN.prj (project) ---

Proj Title=BULLRN
Current Plan=p01
Default Exp/Contr=0,0
English Units
Geom File=g01
Flow File=f01
Plan File=p01
BEGIN DESCRIPTION:
---------- MODELED AS PART OF WVEMD CTP PROGRAM, 2023----------
Stream Name: Bull Run
Flood Zone:  AFH
Upshur County, WV
HEC-RAS Version: RAS 6.3
Vertical Datum: NAVD88
Projection: NAD 1983 StatePlane West Virginia S FIPS 4702 (US Feet)
Terrain: 1-meter LIDAR (FEMA Region III 3DEP collected 2016-2018)
Land Use: 2019 NLCD
Hydrologic Method:
WV SIR2010-5033 regression equations
Additional Model Notes:
None
END DESCRIPTION:
DSS Export Rating Curves= 0
DSS Export Rating Curve Sorted= 0
DSS Export Volume Flow Curves= 0
DXF OffsetX= 0
DXF OffsetY= 0
DXF ScaleX= 0
DXF ScaleY= 0

--- BULLRN.p01 (plan) ---

Plan Title=Floodplain
Program Version=6.30
Short Identifier=Floodplain
Geom File=g01
Flow File=f01
Subcritical Flow
K Sum by GR= 0
Std Step Tol= 0.01
Critical Tol= 0.01
Num of Std Step Trials= 20
Max Error Tol= 0.3
Flow Tol Ratio= 0.001
Split Flow NTrial= 30
Split Flow Tol= 0.02
Split Flow Ratio= 0.02
Log Output Level= 0
Friction Slope Method= 1
Unsteady Friction Slope Method= 2
Unsteady Bridges Friction Slope Method= 1
Parabolic Critical Depth
Global Vel Dist= 0 , 0 , 0
Global Log Level= 0
CheckData=False
Encroach Param=-1 ,0,0, 0
Mapping Interval=1HOUR
Computation Time Step Use Courant=        0
Computation Time Step Use Time Series=    0
Computation Time Step Count To Double=0
Computation Time Step Max Doubling=0
Computation Time Step Max Halving=0
Computation Time Step Residence Courant=0
Run HTab= 0
Run UNet= 0
Run Sediment= 0
Run PostProcess= 0
Run WQNet= 0
Run RASMapper=-1
UNET Theta= 0
UNET Theta Warmup= 0
UNET ZTol= 0
UNET ZSATol= 0
UNET MxIter= 0
UNET Max Iter WO Improvement= 0
UNET MaxInSteps= 0
UNET DtIC= 0
UNET DtMin= 0
UNET MaxCRTS= 0
UNET WFStab= 0
UNET SFStab= 0
UNET WFX= 1
UNET SFX= 1
UNET Gravity=32.17405
UNET 1D Methodology=Finite Difference
UNET DSS MLevel= 1
UNET Pardiso=0
UNET DZMax Abort= 0
UNET Use Existing IB Tables= 0
UNET Froude Reduction=False
UNET Froude Limit= 0
UNET Froude Power= 0
UNET D1 Cores= 0
UNET WindReference=Eulerian
UNET WindDragFormulation=Hsu (1988)
UNET D2 Coriolis=0
UNET D2 Cores= 0
UNET D2 Theta= 1
UNET D2 Theta Warmup= 1
UNET D2 Z Tol= 0.01
UNET D2 Volume Tol= 0.01
UNET D2 Max Iterations= 20
UNET D2 Equation= 0
UNET D2 RampUpFraction=0.1
UNET D2 TimeSlices= 1
UNET D2 Turbulence Formulation=Non-Conservative (original)
UNET D2 Eddy Viscosity=0.3
UNET D2 Transverse Eddy Viscosity=0.1
UNET D2 Smagorinsky Mixing=0
UNET D2 BCVolumeCheck=0
UNET D2 Cores=0
UNET D2 SolverType=PARDISO (Direct)
UNET D2 Minimum Iterations= 3
UNET D2 Maximum Iterations= 30
UNET D2 Restart Number= 10
UNET D2 Relaxation Coeff=1.3
UNET D2 SOR Precondition Iterations= 10
UNET D2 ILUT Maximum Fill= 8
UNET D2 ILUT Tolerance=1E-08
UNET D2 Convergence Tolerance=0.00001
UNET D1D2 MaxIter= 0
UNET D1D2 ZTol=0.01
UNET D1D2 QTol=0.1
UNET D1D2 MinQTol=1
Write IC File= 0
Write IC File at Fixed DateTime=0
Write IC File at Sim End=0
Echo Input=False
Echo Parameters=False
Echo Output=False
Write Detailed= 0
HDF Write Warmup=0
HDF Write Time Slices=0
HDF Flush=0
HDF Compression= 1
HDF Chunk Size= 1
HDF Spatial Parts= 1
HDF Use Max Rows=0
HDF Fixed Rows= 1
Calibration Method= 0
Calibration Iterations= 20
Calibration Max Change=0.05
Calibration Tolerance=0.2
Calibration Maximum=1.5
Calibration Minimum=0.5
Calibration Optimization Method= 1
WQ AD Non Conservative
WQ ULTIMATE=-1
WQ Max Comp Step=1HOUR
WQ Output Interval=15MIN
WQ Output Selected Increments= 0
WQ Output face flow=0
WQ Output face velocity=0
WQ Output face area=0
WQ Output face dispersion=0
WQ Output cell volume=0
WQ Output cell surface area=0
WQ Output cell continuity=0
WQ Output cumulative cell continuity=0
WQ Output face conc=0
WQ Output face dconc_dx=0
WQ Output face courant=0
WQ Output face peclet=0
WQ Output face adv mass=0
WQ Output face disp mass=0
WQ Output cell mass=0
WQ Output cell source sink temp=0
WQ Output nsm pathways=0
WQ Output nsm derived pathways=0
WQ Create Restart=0
WQ Fixed Restart=0
WQ System Summary=0
WQ Write To DSS=0
Sorting and Armoring Iterations= 10
XS Update Threshold= 0.02
Bed Roughness Predictor= 0
Hydraulics Update Threshold= 0.02
Energy Slope Method= 1
Volume Change Method= 1
Sediment Retention Method= 0
Sediment TS Multiplier= 1
Warm Up Method= 0
XS Weighting Method= 0
Number of US Weighted Cross Sections= 1
Number of DS Weighted Cross Sections= 1
Upstream XS Weight=0
Main XS Weight=1
Downstream XS Weight=0
Number of DS XS's Weighted with US Boundary= 1
Upstream Boundary Weight= 1
Weight of XSs Associated with US Boundary= 0
Number of US XS's Weighted with DS Boundary= 1
Downstream Boundary Weight= 0.5
Weight of XSs Associated with DS Boundary= 0.5
Percentile Method= 0
Sediment Output Level= 3
Mass or Volume Output= 0
Output Increment Type= 1
Profile and TS Output Increment= 1
Transport Output Increment 1
XS Output Flag= 0
XS Output Increment= 10
Read HDF5 Sediment Hotstart= 0
Sediment Hotstart Type= 0
Write Gradation File= 0
Read Gradation Hotstart= 0
Write HDF5 File= 1
Write Binary Output= 1
Write DSS Sediment File= 0
DSS Sediment Output Type= 1
SV Curve= 0
Specific Gage Flag= 0
Subcell Erosion Methods= 0
Subcell Deposition Methods= 0
Advection Scheme= 1
Matrix Solver= 0
Implicit Weighting Factor= 1
Maximum Outer Loop Convergence Iterations= 5
Convergence Maximum Absolute= 0.001
Convergence RMSE= 0.0001
Grain Fractions Max Abs Error= 0.001
Max Subgrid Regions= 1
Max Subgrid Length Scale= 3.402823E+38
Initial Layer Thickness= 3.402823E+38
Min Layer Thickness= 3.402823E+38
Max Layer Thickness= 3.402823E+38
Number of Layers= 5

--- BULLRN.f01 (steady flow) ---

Flow Title=Flows
Program Version=6.30
Number of Profiles= 1
Profile Names=01pct
River Rch & RM=BULLRN,Main,12562
     541
River Rch & RM=BULLRN,Main,6959
     652
River Rch & RM=BULLRN,Main,4989
     934
River Rch & RM=BULLRN,Main,1086
    1060
Boundary for River Rch & Prof#=BULLRN,Main            , 1
Up Type= 0
Dn Type= 3
Dn Slope=0.00165
DSS Import GetInterval= 0
DSS Import GetPeak= 0
DSS Import FillOption= 0

--- BULLRN.g01 (geometry) ---

Geom Title=Geometry
Program Version=6.31

River Reach=BULLRN          ,Main
Reach XY= 30
2166255.96590681698771.027595738     2166891.948      698690.853
     2167258.725      698447.184     2167640.896      698389.121
     2167731.496      698179.993     2167885.195      698127.968
     2167904.854      698256.399     2168201.778      698107.708
     2168492.463      697886.532     2168461.672      697701.727
     2168594.767      697469.963     2169705.283      696288.993
     2170567.294      695758.245       2171025.9      695677.404
     2171098.214      695429.9582171244.88679099695348.216489726
     2171682.589      695351.606     2171695.581      695199.339
2171853.11215578695135.826807294 2171864.2383958694889.868912359
     2171971.758      694931.146     2172161.198      694788.207
     2172265.705      694932.977     2172802.549      694794.502
     2172820.663      694691.5122173186.89977842694751.958735546
      2173475.12      694580.337     2174287.997      694565.686
     2174850.137      694076.374     2175187.868      694094.832

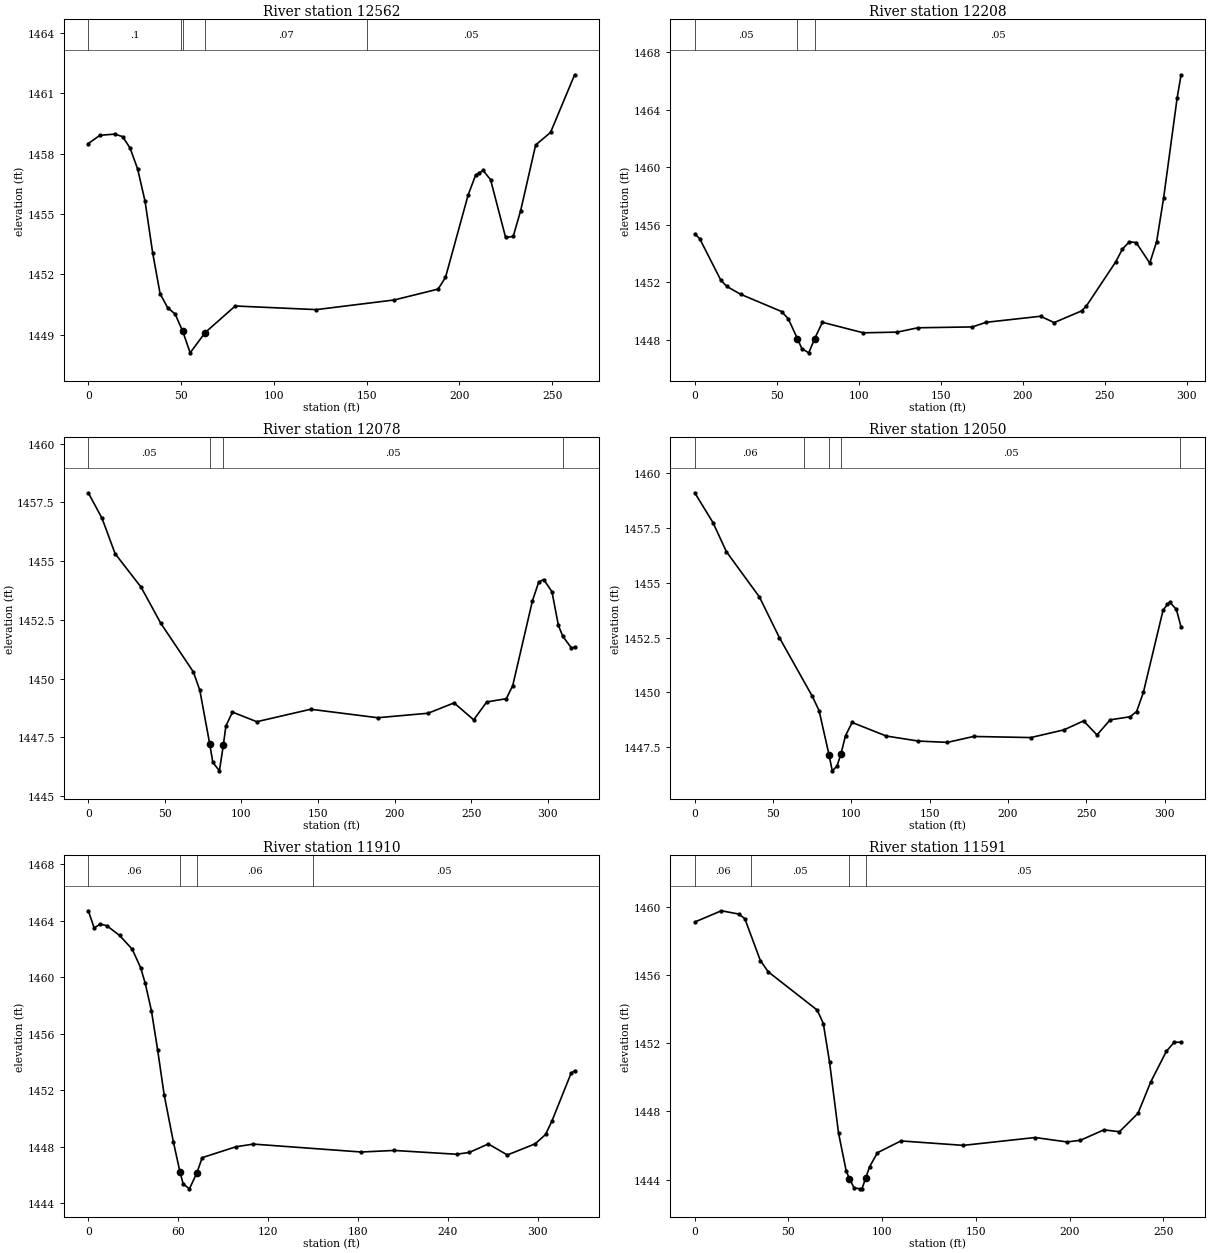
Type RM Length L Ch R = 1 ,12562   ,354.2,354.2,354.2
XS GIS Cut Line= 3
2166270.27404362698827.4257651622166234.00371295698594.764863562
2166235.77299738 698568.22559722
#Sta/Elev= 30
       0  1458.5     6.3 1458.91    14.4 1458.97    18.5 1458.84    22.5 1458.28
    26.6 1457.23    30.6 1455.62    34.7 1453.06    38.7 1451.03    42.8 1450.33
    46.8 1450.02    50.9 1449.16    54.9 1448.09      63  1449.1    79.2 1450.42
   122.9 1450.24   164.9 1450.72   188.5 1451.26   192.5 1451.84   204.7 1455.94
   208.7 1456.92   210.4 1457.03   212.8 1457.16   216.8  1456.7   224.9 1453.83
     229 1453.88     233 1455.16   241.1 1458.43   249.1 1459.05   262.1 1461.92
#Mann= 5 ,-1,0
       0      .1       0      50     .07       0    50.9    .045       0
      63     .07       0     150     .05       0
Bank Sta=50.9,63
XS Rating Curve= 0 ,0
Exp/Cntr(USF)=0,0
Exp/Cntr=0.3,0.1

Type RM Length L Ch R = 1 ,12208   ,129.5,129.5,129.5
XS GIS Cut Line= 3
2166624.08049673698780.0514937392166553.69744013698531.283793686
2166542.77593135 698494.87876441
#Sta/Elev= 30
       0 1455.37       3 1455.04    15.9 1452.15    19.6 1451.72    27.9 1451.18
    52.9 1449.98      57 1449.48    62.61448.091    65.3  1447.4    69.5 1447.11
    73.11448.094    77.8 1449.23   102.8  1448.5   123.5 1448.55     136 1448.85
   169.3 1448.91   177.6 1449.23   210.8 1449.65   219.1 1449.21   235.8 1450.02
   238.8 1450.37   256.6 1453.42   260.7 1454.31   264.9 1454.82   269.1 1454.77
   277.4 1453.34   281.6 1454.84   285.8 1457.83   294.1 1464.82   296.5 1466.42
#Mann= 3 ,-1,0
       0     .05       0    62.6    .045       0    73.1     .05       0
Bank Sta=62.6,73.1
XS Rating Curve= 0 ,0
Exp/Cntr(USF)=0,0
Exp/Cntr=0.3,0.1

Type RM Length L Ch R = 1 ,12078   ,28.3,28.3,28.3
XS GIS Cut Line= 2
2166760.76587811  698769.61380882166652.22850594698471.281138766
#Sta/Elev= 30
       0 1457.91       9 1456.82    17.5 1455.32    34.5 1453.89    47.3 1452.36
    68.6 1450.29    72.8 1449.51    79.31447.216    81.3 1446.44    85.6 1446.08
    88.2 1447.19    89.8 1447.98    94.1 1448.58     110 1448.17   145.2  1448.7
   188.9 1448.34   221.8 1448.53   238.8 1448.97   251.6 1448.25   260.1 1449.01
   272.9 1449.15   277.1 1449.71   289.9  1453.3   294.1 1454.12   297.3 1454.22
   302.7  1453.7   306.9 1452.27   309.8  1451.8   315.4 1451.31   317.5 1451.34
#Mann= 4 ,-1,0
       0     .05       0    79.3    .045       0    88.2     .05       0
     310      .1       0
Bank Sta=79.3,88.2
XS Rating Curve= 0 ,0
Exp/Cntr(USF)=0,0
Exp/Cntr=0.3,0.1

Type RM Length L Ch R = 1 ,12050   ,139.9,139.9,139.9
XS GIS Cut Line= 2
2166788.27771637698768.2881720412166687.94615173698474.328445516
#Sta/Elev= 30
       0 1459.11    11.7 1457.74    20.2 1456.42    41.3 1454.35      54  1452.5
    75.1 1449.81    79.4 1449.16    85.71447.156    87.8 1446.41    90.8 1446.62
    93.41447.191    96.3 1448.02   100.5 1448.62   122.3    1448   142.8 1447.77
   161.3 1447.71   178.1 1447.98   214.6 1447.93   235.7 1448.28   248.3 1448.69
   256.9 1448.05   265.3 1448.74     278 1448.88   282.2 1449.12   286.5 1449.99
   299.1 1453.75   301.9 1454.01   303.4 1454.11   307.6 1453.78   310.6 1452.97
#Mann= 5 ,-1,0
       0     .06       0      70     .05       0    85.7    .045       0
    93.4     .05       0     310      .1       0
Bank Sta=85.7,93.4
XS Rating Curve= 0 ,0
Exp/Cntr(USF)=0,0
Exp/Cntr=0.3,0.1

Type RM Length L Ch R = 1 ,11910   ,318.8,318.8,318.8
XS GIS Cut Line= 2
2166917.00908451698752.8443927332166808.86867084698446.853066712
#Sta/Elev= 30
       0 1464.71     3.9  1463.5     8.1 1463.77    12.4 1463.65    20.9 1462.96
    29.3 1461.99    34.9 1460.68      38 1459.57    42.1 1457.64    46.3 1454.83
    50.6 1451.68    56.8 1448.32    61.2  1446.2    63.3 1445.36    67.5 1445.01
    72.5 1446.16      76 1447.22    98.5 1447.99   110.1 1448.18   182.1 1447.62
   204.1 1447.73   245.7 1447.46   254.2 1447.59   266.9 1448.19   279.6 1447.41
   298.2  1448.2   305.1 1448.86   309.3  1449.8   322.1 1453.19   324.5 1453.38
#Mann= 4 ,-1,0
       0     .06       0    61.2    .045       0    72.5     .06       0
     150     .05       0
Bank Sta=61.2,72.5
XS Rating Curve= 0 ,0
Exp/Cntr(USF)=0,0
Exp/Cntr=0.3,0.1

Type RM Length L Ch R = 1 ,11591   ,289.9,289.9,289.9
XS GIS Cut Line= 2
2167163.60116655698606.8103649012167091.20961267698357.647424457
#Sta/Elev= 30
       0 1459.11    14.2 1459.77    23.4 1459.58    26.7 1459.31      35 1456.85
    39.2 1456.19    65.4 1453.94    68.6 1453.15    71.9 1450.91    76.7 1446.74
    80.8 1444.51    82.51444.058      85 1443.52      88 1443.46    89.2 1443.46
    91.2 1444.09    93.3 1444.76    97.5 1445.58     110 1446.27   143.3 1446.01
   181.6 1446.47   198.7 1446.21   205.8 1446.31   218.3 1446.92   226.6 1446.81
   236.5 1447.89   243.3 1449.73   251.6 1451.52   255.8 1452.06   259.5 1452.06
#Mann= 4 ,-1,0
       0     .06       0      30     .05       0    82.5    .045       0
    91.2     .05       0
Bank Sta=82.5,91.2
XS Rating Curve= 0 ,0
Exp/Cntr(USF)=0,0
Exp/Cntr=0.3,0.1

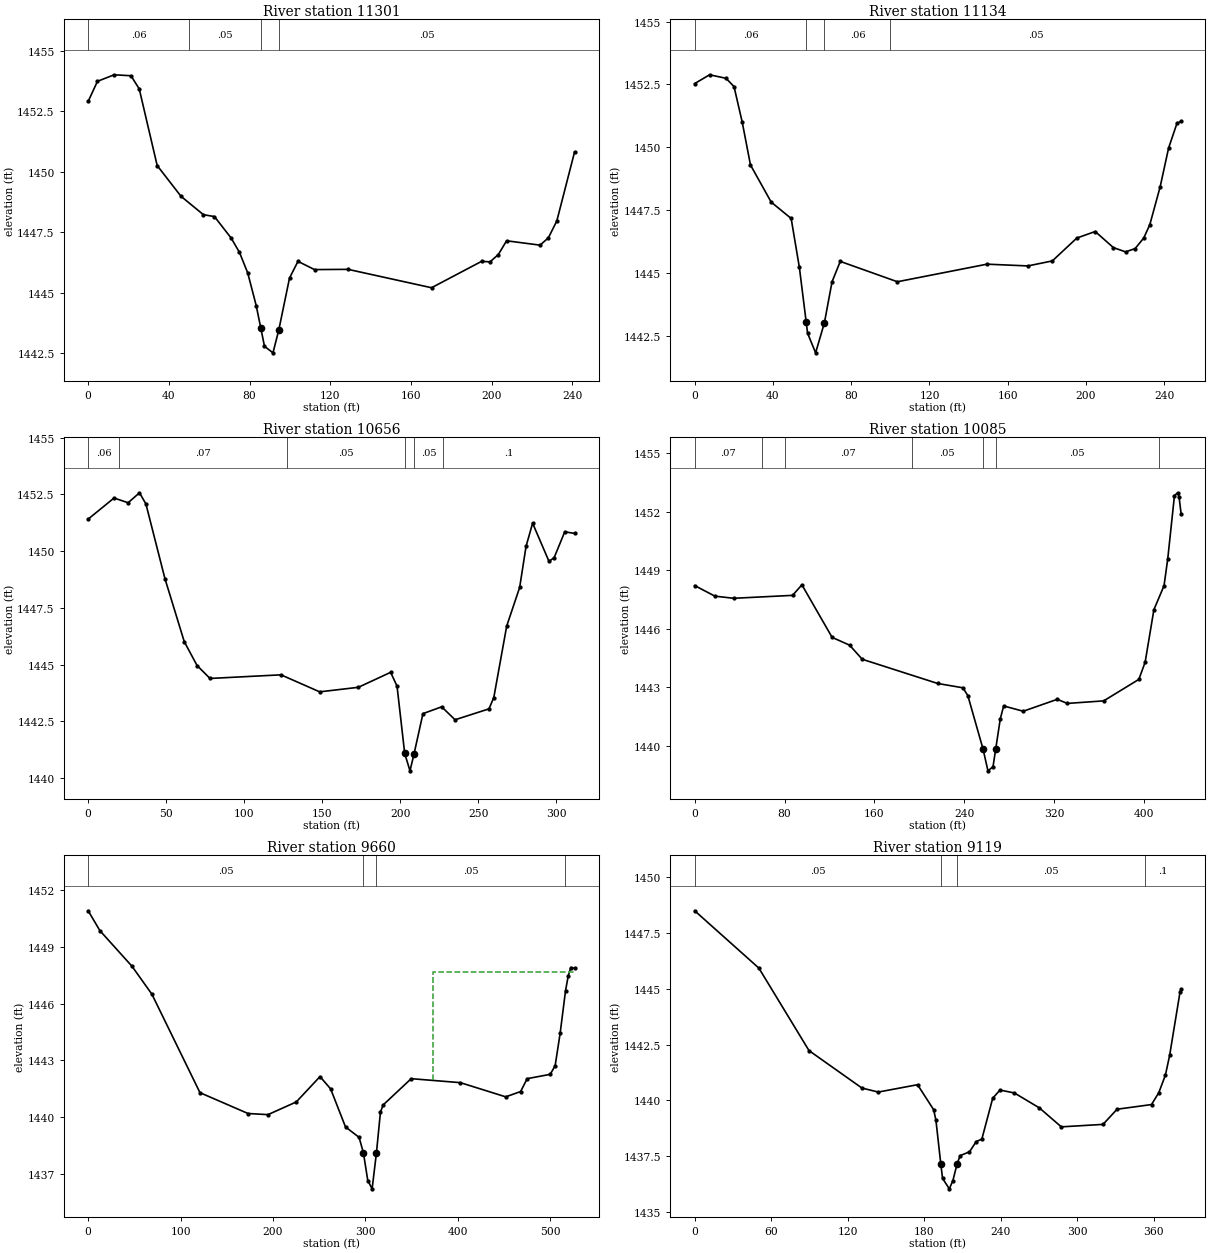
Type RM Length L Ch R = 1 ,11301   ,167.6,167.6,167.6
XS GIS Cut Line= 2
2167389.59080593698525.6595588612167327.63495166698292.655106433
#Sta/Elev= 30
       0 1452.91     4.6 1453.74    12.9 1454.01    21.2 1453.97    25.3 1453.43
    34.2 1450.26      46 1448.99    57.1 1448.23    62.6 1448.15    70.9 1447.26
      75 1446.67    79.1 1445.82    83.3 1444.47    85.61443.529    87.4 1442.79
    91.6 1442.52    94.5 1443.47    99.8 1445.61     104  1446.3   112.2 1445.96
   128.8 1445.97   170.2 1445.21     195  1446.3   199.2 1446.28   203.3 1446.58
   207.4 1447.15     224 1446.97   228.1 1447.27   232.3 1447.97   241.1 1450.82
#Mann= 4 ,-1,0
       0     .06       0      50     .05       0    85.6    .045       0
    94.5     .05       0
Bank Sta=85.6,94.5
XS Rating Curve= 0 ,0
Exp/Cntr(USF)=0,0
Exp/Cntr=0.3,0.1

Type RM Length L Ch R = 1 ,11134   ,478.2,478.2,478.2
XS GIS Cut Line= 3
2167535.25686182698480.4878018312167477.89494708698286.380389143
2167461.49562732698243.177920192
#Sta/Elev= 30
       0 1452.53     7.6 1452.88      16 1452.74    20.1 1452.41    24.3 1450.99
    28.5 1449.29    39.1 1447.81    49.3 1447.16    53.5 1445.21      571443.024
    57.7 1442.59    61.8 1441.81    66.3 1443.01    70.2 1444.64    74.4 1445.45
   103.6 1444.64   149.4 1445.34   170.3 1445.27   182.8 1445.47   195.3 1446.38
   204.7 1446.64     214    1446   220.2 1445.83   225.1 1445.96   229.5 1446.38
   232.6 1446.91   237.9 1448.42   242.2 1449.96   246.5 1450.95   248.6 1451.03
#Mann= 4 ,-1,0
       0     .06       0      57    .045       0    66.3     .06       0
     100     .05       0
Bank Sta=57,66.3
XS Rating Curve= 0 ,0
Exp/Cntr(USF)=0,0
Exp/Cntr=0.3,0.1

Type RM Length L Ch R = 1 ,10656   ,570.3,570.3,570.3
XS GIS Cut Line= 3
2167825.50443443698405.5653760362167817.14647636698358.551861889
 2167750.2828118698103.111768355
#Sta/Elev= 30
       0 1451.41    16.6 1452.34    25.6 1452.13    32.9 1452.57      37 1452.08
    49.2 1448.79    61.6 1446.01    69.8 1444.96    78.1 1444.39   123.6 1444.55
   148.4  1443.8   173.2    1444   193.9 1444.66     198 1444.05   202.91441.089
   206.3 1440.32   208.91441.068   214.6 1442.84   226.6 1443.14   235.2 1442.57
   256.9 1443.05     260 1443.54   268.3  1446.7   276.6  1448.4   280.7 1450.21
   284.9 1451.23   295.4 1449.55   298.7 1449.71   305.5 1450.85   311.8 1450.78
#Mann= 6 ,-1,0
       0     .06       0      20     .07       0  127.75     .05       0
   202.9    .045       0   208.9     .05       0  227.75      .1       0
Bank Sta=202.9,208.9
XS Rating Curve= 0 ,0
Exp/Cntr(USF)=0,0
Exp/Cntr=0.3,0.1

Type RM Length L Ch R = 1 ,10085   ,425.5,425.5,425.5
XS GIS Cut Line= 3
2168153.81204834 698363.647908822168142.24115769 698271.23782621
2167989.82255715697967.619193617
#Sta/Elev= 30
       0 1448.21      18 1447.67    34.7 1447.56    87.1 1447.71    95.4 1448.25
   122.3 1445.56   137.9 1445.16   149.1 1444.44   216.3  1443.2   238.7 1442.98
   243.1 1442.58   256.6 1439.85     261 1438.73   265.5 1438.94   267.91439.847
     272  1441.4     275 1442.05   292.4 1441.78   322.7 1442.39   331.6 1442.18
     364 1442.31   395.3 1443.41   400.9 1444.29   408.7 1446.98   417.7  1448.2
     421 1449.57     427 1452.82   429.9 1452.96   431.1 1452.74   432.9 1451.89
#Mann= 7 ,-1,0
       0     .07       0      60     .05       0      80     .07       0
  193.13     .05       0   256.6    .045       0   267.9     .05       0
  413.13      .1       0
Bank Sta=256.6,267.9
XS Rating Curve= 0 ,0
Exp/Cntr(USF)=0,0
Exp/Cntr=0.3,0.1

Type RM Length L Ch R = 1 ,9660    ,540.3,540.3,540.3
XS GIS Cut Line= 4
2168607.90833753698051.3380793632168375.29478665697954.713777182
2168252.69322653 697878.991440772168166.10072637697781.526140741
#Sta/Elev= 30
       0  1450.9    12.7 1449.85    47.4 1447.97      69 1446.49     121 1441.29
     173 1440.19   194.6 1440.13   225.2  1440.8   250.9 1442.14   262.4 1441.49
   278.5 1439.48   293.2 1438.93   297.9 1438.11   302.6 1436.65   307.3 1436.21
     312 1438.12   316.3 1440.26   319.2 1440.64   349.6 1442.03   402.8 1441.82
   451.9 1441.07     468 1441.35   475.1 1442.03   500.1 1442.26   505.4 1442.72
   510.8 1444.43   516.6 1446.67   519.5 1447.45   522.3  1447.9   526.4 1447.86
#Mann= 4 ,-1,0
       0     .05       0   297.9    .045       0     312     .05       0
  515.98      .1       0
#XS Ineff= 2 , 0
                          372.68         1447.65
Permanent Ineff=
       F       F
Bank Sta=297.9,312
XS Rating Curve= 0 ,0
Exp/Cntr(USF)=0,0
Exp/Cntr=0.3,0.1

Type RM Length L Ch R = 1 ,9119    ,235.9,235.9,235.9
XS GIS Cut Line= 4
2168731.49107926697736.545391465 2168566.5243952697676.935757137
 2168515.4914679697633.0364648352168419.61042528697532.920564103
#Sta/Elev= 30
       0  1448.5    50.3 1445.93    89.6 1442.23   131.1 1440.55   143.9 1440.37
   174.7  1440.7   187.3 1439.58   189.1 1439.11   192.91437.156   194.3  1436.5
   199.6 1436.03   202.4  1436.4   205.7 1437.15   208.1 1437.52   215.4 1437.69
   220.7 1438.15   225.1 1438.26   233.6 1440.09   239.3 1440.46   250.6 1440.33
   270.2 1439.66   287.4 1438.81   320.1 1438.92   331.1  1439.6   358.1 1439.81
   363.8 1440.34     369 1441.13   372.3 1442.01   380.5 1444.87   381.3 1444.98
#Mann= 4 ,-1,0
       0     .05       0   192.9    .045       0   205.7     .05       0
  352.72      .1       0
Bank Sta=192.9,205.7
XS Rating Curve= 0 ,0
Exp/Cntr(USF)=0,0
Exp/Cntr=0.3,0.1

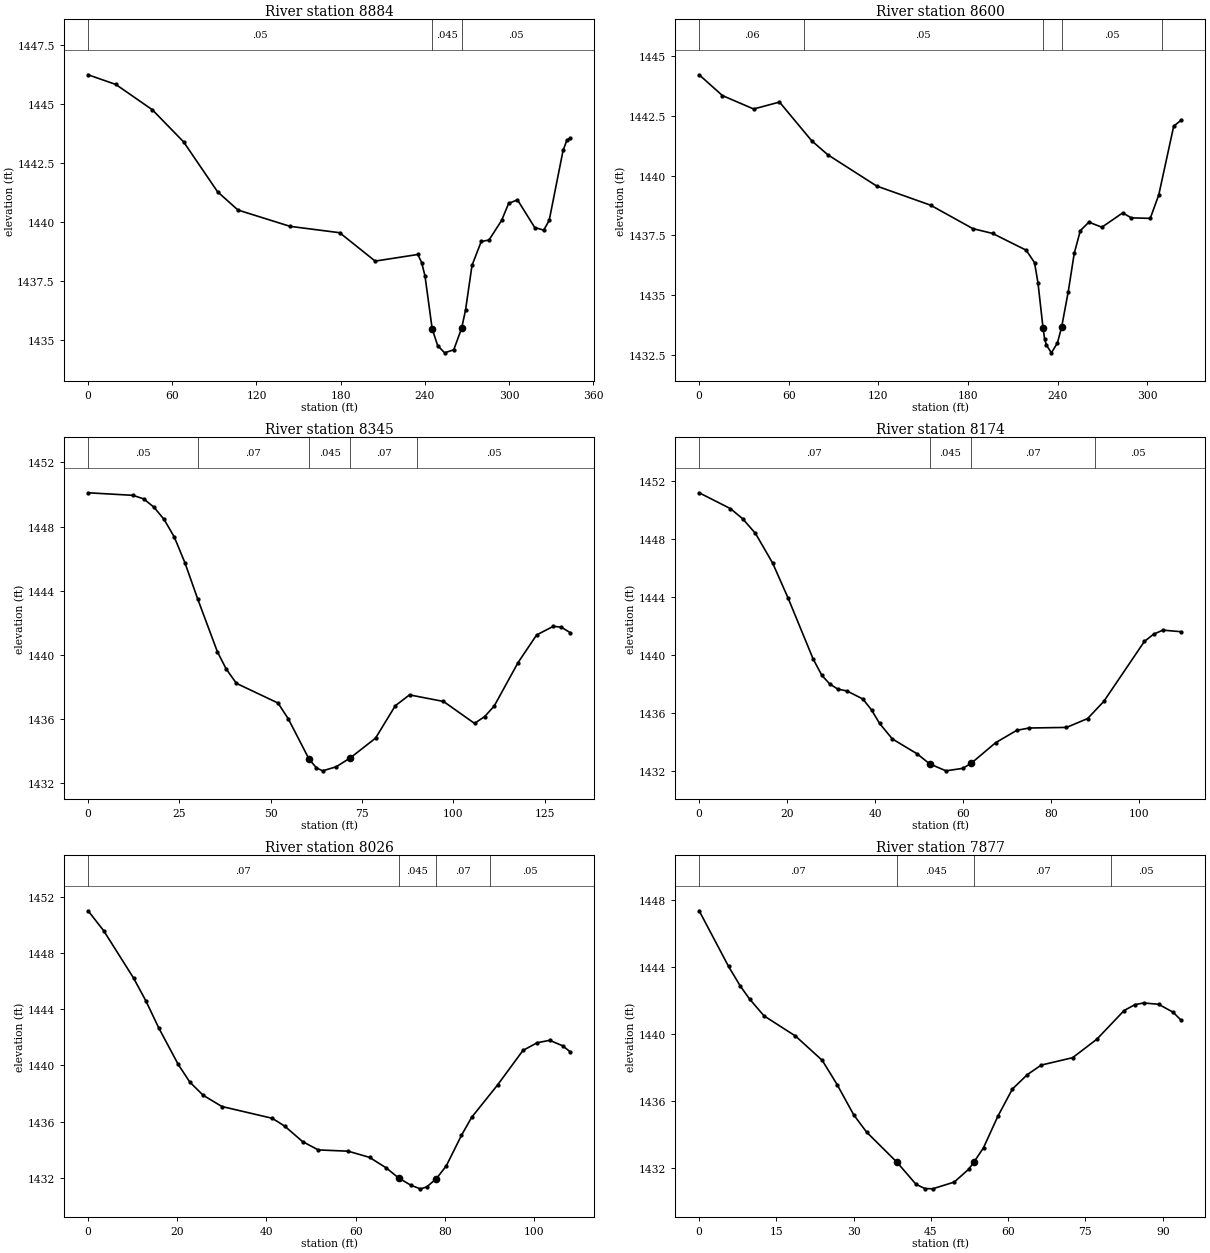
Type RM Length L Ch R = 1 ,8884    ,284,284,284
XS GIS Cut Line= 4
2168771.42732699697649.5284900692168696.72420691697539.439681538
2168556.94133865 697430.849824152168546.61286498697398.927505901
#Sta/Elev= 30
       0 1446.22    19.8 1445.81    45.8 1444.74    68.1 1443.38    92.3 1441.27
   106.8  1440.5   143.9 1439.81   179.3 1439.54   204.6 1438.34     235 1438.62
   237.7 1438.28   240.1 1437.71   245.2 1435.48   249.1 1434.77   254.1 1434.46
   260.6 1434.59   266.2  1435.5     269 1436.27   273.6 1438.16   280.2 1439.17
   285.7 1439.23   294.7 1440.06   299.7 1440.78     306 1440.93   318.3 1439.76
   324.7 1439.65   328.6 1440.06   338.5 1443.02   341.2 1443.45   343.6 1443.54
#Mann= 3 ,-1,0
       0     .05       0   245.2    .045       0   266.2     .05       0
Bank Sta=245.2,266.2
XS Rating Curve= 0 ,0
Exp/Cntr(USF)=0,0
Exp/Cntr=0.3,0.1

Type RM Length L Ch R = 1 ,8600    ,254.1,254.1,254.1
XS GIS Cut Line= 3
 2168922.8753729697462.8931145162168884.93771289697370.758797338
2168726.41249068697213.588491562
#Sta/Elev= 30
       0 1444.21    15.6 1443.34    36.5 1442.78    53.8 1443.07    75.4 1441.45
    86.1 1440.87   118.9 1439.56     155 1438.76   183.3 1437.78   196.5 1437.58
     219 1436.88   224.6 1436.36   226.9 1435.52   230.3 1433.63   231.4 1433.15
   232.6 1432.91   235.9 1432.59   239.9    1433   242.7 1433.65   247.2 1435.15
   251.2 1436.75   255.3  1437.7     261 1438.05   269.7 1437.84   283.7 1438.44
   289.4 1438.23   302.1 1438.21   307.8 1439.19   317.8 1442.06   322.9 1442.32
#Mann= 5 ,-1,0
       0     .06       0      70     .05       0   230.3    .045       0
   242.7     .05       0  309.64     .07       0
Bank Sta=230.3,242.7
XS Rating Curve= 0 ,0
Exp/Cntr(USF)=0,0
Exp/Cntr=0.3,0.1

Type RM Length L Ch R = 1 ,8345    ,171.6,171.6,171.6
XS GIS Cut Line= 2
2168991.38877656697127.3742184152168902.56066938697029.794340236
#Sta/Elev= 30
       0 1450.11    12.3 1449.95    15.2 1449.73      18 1449.22    20.8 1448.45
    23.6 1447.35    26.5 1445.75      30 1443.49    35.4 1440.19    37.8 1439.12
    40.6 1438.22      52 1436.99    54.8 1436.01    60.5 1433.49    62.5 1432.95
    64.2 1432.76    67.9 1433.01    71.8 1433.57    78.7  1434.8    84.1 1436.82
      88  1437.5    97.3 1437.09   105.8 1435.72   108.6 1436.15   111.2 1436.81
   117.7 1439.51   122.8 1441.24   127.4 1441.78   129.6 1441.72     132 1441.38
#Mann= 5 ,-1,0
       0     .05       0      30     .07       0    60.5    .045       0
    71.8     .07       0      90     .05       0
Bank Sta=60.5,71.8
XS Rating Curve= 0 ,0
Exp/Cntr(USF)=0,0
Exp/Cntr=0.3,0.1

Type RM Length L Ch R = 1 ,8174    ,147.4,147.4,147.4
XS GIS Cut Line= 2
2169096.00216466  696991.4009129 2169018.2267215696914.205883496
#Sta/Elev= 30
       0 1451.19     7.1  1450.1     9.9  1449.4    12.8 1448.39    16.7 1446.35
    20.2 1443.95    25.9 1439.75    27.9 1438.61    29.7 1438.02    31.5 1437.67
    33.6 1437.54    37.2 1436.99    39.2 1436.23      41 1435.31    43.9 1434.24
    49.5 1433.22    52.4 1432.52    56.1 1432.04    59.9 1432.21    61.8 1432.55
    67.4 1433.98    72.2 1434.83      75 1434.99    83.5 1435.03    88.3 1435.64
      92 1436.83   101.2 1440.95   103.3 1441.45   105.4 1441.73   109.6 1441.62
#Mann= 4 ,-1,0
       0     .07       0    52.4    .045       0    61.8     .07       0
      90     .05       0
Bank Sta=52.4,61.8
XS Rating Curve= 0 ,0
Exp/Cntr(USF)=0,0
Exp/Cntr=0.3,0.1

Type RM Length L Ch R = 1 ,8026    ,149,149,149
XS GIS Cut Line= 2
  2169192.071493 696887.692129352169116.84987037696810.119831004
#Sta/Elev= 30
       0    1451     3.5 1449.58    10.2 1446.21      13 1444.56    15.8 1442.69
    20.2 1440.07    22.8 1438.81    25.8 1437.87      30 1437.07    41.3 1436.23
    44.1 1435.67    48.1 1434.57    51.6 1433.98    58.3 1433.89    63.1 1433.45
    66.8 1432.71    69.6 1431.99    72.4 1431.46    74.5 1431.21    75.9 1431.34
    78.1 1431.94    80.3 1432.84    83.7 1435.01      86  1436.3    91.8  1438.6
    97.5 1441.06   100.7 1441.61   103.5 1441.78   106.4 1441.39   108.1 1440.96
#Mann= 4 ,-1,0
       0     .07       0    69.6    .045       0    78.1     .07       0
      90     .05       0
Bank Sta=69.6,78.1
XS Rating Curve= 0 ,0
Exp/Cntr(USF)=0,0
Exp/Cntr=0.3,0.1

Type RM Length L Ch R = 1 ,7877    ,137,137,137
XS GIS Cut Line= 2
2169286.22382637696768.9707480612169215.89593444696707.279614795
#Sta/Elev= 30
       0 1447.33     5.7 1444.02       8 1442.84     9.8 1442.07    12.6 1441.07
    18.7 1439.87    23.9 1438.42    26.8 1436.97      30 1435.18    32.5 1434.15
    38.41432.355    42.1 1431.04    43.8 1430.79    45.3 1430.77    49.5 1431.17
    52.3 1431.93    53.41432.386    55.2 1433.22      58  1435.1    60.8 1436.71
    63.7 1437.57    66.4 1438.14    72.5 1438.58    77.2 1439.68    82.5 1441.39
    84.6 1441.74    86.3 1441.84    89.2 1441.76      92 1441.29    93.6  1440.8
#Mann= 4 ,-1,0
       0     .07       0    38.4    .045       0    53.4     .07       0
      80     .05       0
Bank Sta=38.4,53.4
XS Rating Curve= 0 ,0
Exp/Cntr(USF)=0,0
Exp/Cntr=0.3,0.1

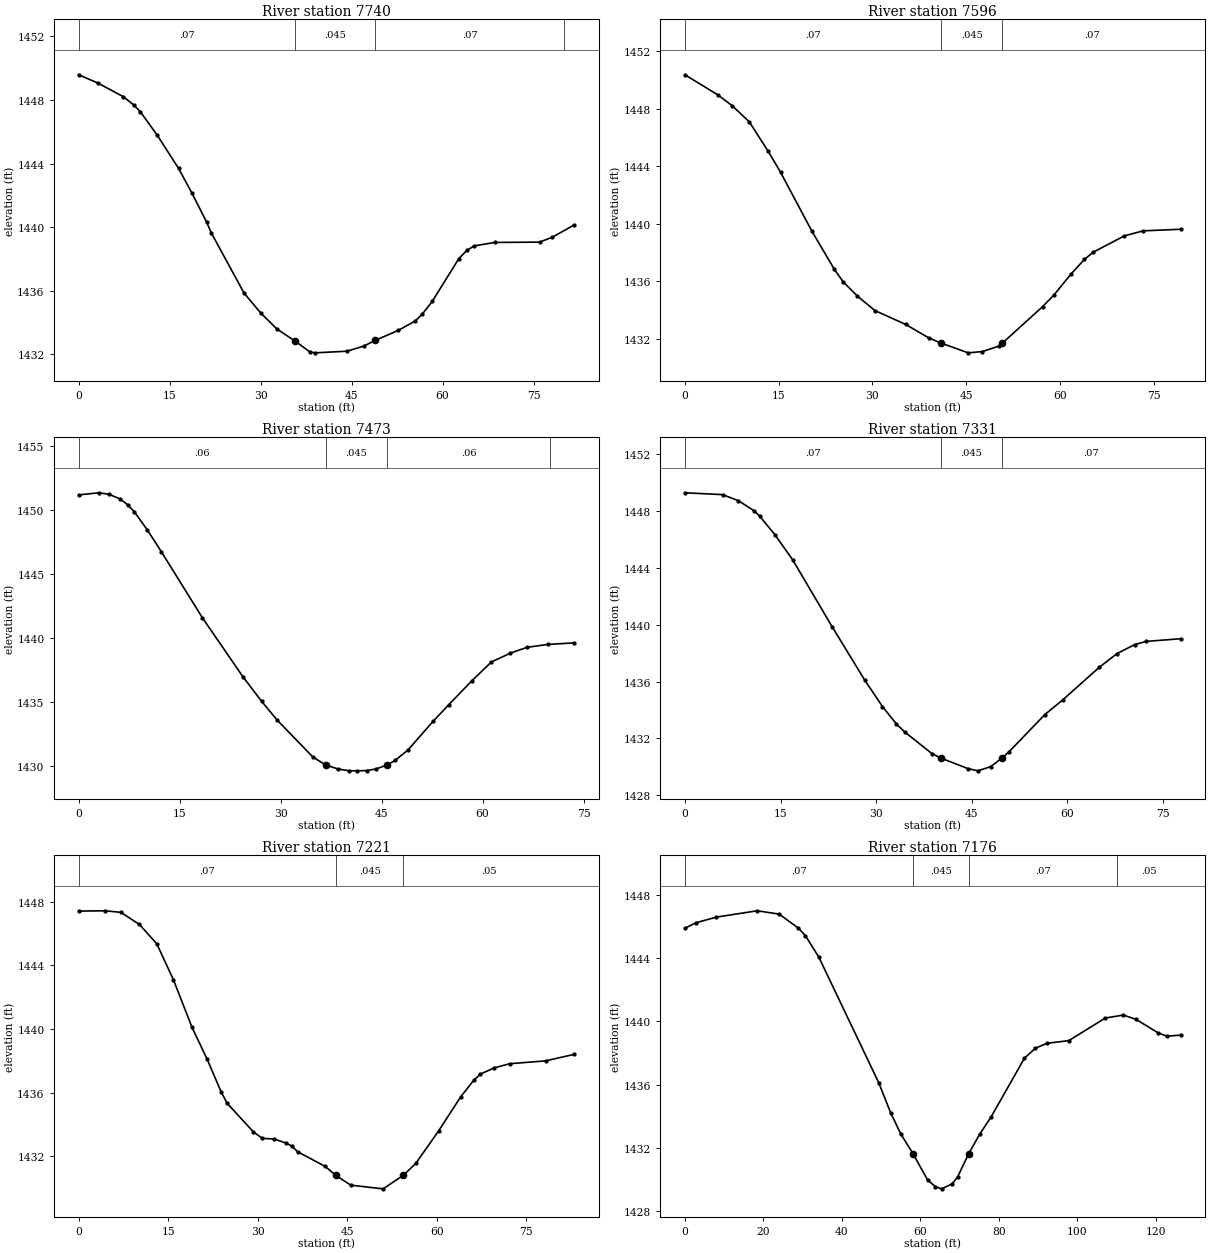
Type RM Length L Ch R = 1 ,7740    ,144.1,144.1,144.1
XS GIS Cut Line= 2
 2169384.4113156 696675.33097008  2169323.954005696620.425861473
#Sta/Elev= 30
       0 1449.58     3.2 1449.06     7.4  1448.2     9.2 1447.65    10.2 1447.25
      13 1445.77    16.5 1443.69    18.7 1442.14    21.1 1440.33    21.9 1439.63
    27.3 1435.85      30 1434.62    32.7  1433.6    35.7 1432.84    38.1 1432.17
    38.9  1432.1    44.2  1432.2      47 1432.52    48.9 1432.88    52.7 1433.51
    55.5  1434.1    56.7 1434.55    58.3 1435.33    62.7 1438.03      64 1438.54
    65.2 1438.82    68.6 1439.04      76 1439.06    78.1 1439.37    81.7 1440.14
#Mann= 4 ,-1,0
       0     .07       0    35.7    .045       0    48.9     .07       0
      80     .05       0
Bank Sta=35.7,48.9
XS Rating Curve= 0 ,0
Exp/Cntr(USF)=0,0
Exp/Cntr=0.3,0.1

Type RM Length L Ch R = 1 ,7596    ,123.8,123.8,123.8
XS GIS Cut Line= 2
2169488.38399258696571.5643977652169424.97921672696523.925133743
#Sta/Elev= 26
       0 1450.38     5.3 1448.97     7.6 1448.21    10.3  1447.1    13.3 1445.06
    15.3 1443.59    20.3  1439.5    23.9 1436.84    25.3 1435.98    27.6 1434.97
    30.4 1433.97    35.3 1433.01      39 1432.07    40.91431.722    45.3 1431.03
    47.6 1431.12    50.3 1431.51    50.81431.714    57.2 1434.24      59 1435.04
    61.8 1436.53    63.9 1437.53    65.3 1438.03    70.3 1439.17    73.3 1439.52
    79.3 1439.63
#Mann= 3 ,-1,0
       0     .07       0    40.9    .045       0    50.8     .07       0
Bank Sta=40.9,50.8
XS Rating Curve= 0 ,0
Exp/Cntr(USF)=0,0
Exp/Cntr=0.3,0.1

Type RM Length L Ch R = 1 ,7473    ,141.9,141.9,141.9
XS GIS Cut Line= 2
2169570.46990955696485.2477409812169514.90980866696436.961100869
#Sta/Elev= 30
       0  1451.2       3 1451.37     4.5 1451.26     6.2 1450.88     7.3 1450.43
     8.3 1449.87    10.2 1448.48    12.3 1446.76    18.4 1441.59    24.4 1436.99
    27.2 1435.05    29.5 1433.59    34.8  1430.7    36.7 1430.08    38.5 1429.77
    40.1 1429.63    41.4 1429.62    42.8 1429.64    44.2 1429.77    45.81430.078
      47 1430.43    48.9 1431.24    52.7 1433.52      55  1434.8    58.4 1436.66
    61.3 1438.13    64.1 1438.82    66.6 1439.28    69.7 1439.51    73.6 1439.63
#Mann= 4 ,-1,0
       0     .06       0    36.7    .045       0    45.8     .06       0
      70     .07       0
Bank Sta=36.7,45.8
XS Rating Curve= 0 ,0
Exp/Cntr(USF)=0,0
Exp/Cntr=0.3,0.1

Type RM Length L Ch R = 1 ,7331    ,109.2,109.2,109.2
XS GIS Cut Line= 2
2169668.33794195696388.9029464372169613.88218851696333.304764605
#Sta/Elev= 26
       0 1449.27     5.9 1449.14     8.4 1448.71    10.8 1448.02    11.7 1447.64
    14.1 1446.33    16.9 1444.56    23.1 1439.85    28.2 1436.11      31 1434.24
    33.2 1433.01    34.5 1432.45    38.8 1430.92    40.2 1430.61    44.4 1429.88
      46 1429.72      48 1430.02    49.71430.598    50.8 1431.03    56.5 1433.68
    59.3 1434.71      65 1436.99    67.8 1437.96    70.6  1438.6    72.4 1438.82
    77.8 1439.01
#Mann= 3 ,-1,0
       0     .07       0    40.2    .045       0    49.7     .07       0
Bank Sta=40.2,49.7
XS Rating Curve= 0 ,0
Exp/Cntr(USF)=0,0
Exp/Cntr=0.3,0.1

Type RM Length L Ch R = 1 ,7221    ,45.1,45.1,45.1
XS GIS Cut Line= 2
2169749.00660843696318.7474868632169692.86767716 696257.67326493
#Sta/Elev= 30
       0 1447.41     4.5 1447.43     7.1 1447.33    10.2 1446.57    13.1 1445.36
    15.9 1443.09      19 1440.11    21.5 1438.14    23.9 1436.04    24.9 1435.33
    29.3 1433.53    30.8 1433.13    32.8 1433.09    34.7 1432.84    35.7 1432.65
    36.7 1432.29    41.3 1431.37    43.11430.802    45.6 1430.19      51 1429.96
    54.4 1430.81    56.5 1431.57    60.3  1433.6      64 1435.74    66.2 1436.79
    67.3 1437.17    69.6 1437.56    72.2 1437.82    78.2    1438      83 1438.41
#Mann= 3 ,-1,0
       0     .07       0    43.1    .045       0    54.4     .05       0
Bank Sta=43.1,54.4
XS Rating Curve= 0 ,0
Exp/Cntr(USF)=0,0
Exp/Cntr=0.3,0.1

Type RM Length L Ch R = 1 ,7176    ,30,30,30
XS GIS Cut Line= 2
2169791.87111409696303.3220160742169710.74727384696206.466936848
#Sta/Elev= 30
       0  1445.9     2.8 1446.24       8  1446.6    18.4    1447      24 1446.79
    28.9  1445.9    30.7 1445.42    34.1 1444.07    49.4  1436.1    52.4 1434.22
      55 1432.87    58.1 1431.63    61.8 1429.97    63.8 1429.54    65.4  1429.4
    68.1 1429.72    69.5 1430.17    72.3 1431.63    75.1 1432.86      78 1433.95
    86.5 1437.67    89.3  1438.3    92.2 1438.61    97.8 1438.78   107.1 1440.21
   111.7  1440.4   114.9 1440.13   120.6 1439.27   122.8 1439.06   126.3 1439.13
#Mann= 4 ,-1,0
       0     .07       0    58.1    .045       0    72.3     .07       0
     110     .05       0
Bank Sta=58.1,72.3
XS Rating Curve= 0 ,0
Exp/Cntr(USF)=0,0
Exp/Cntr=0.3,0.1

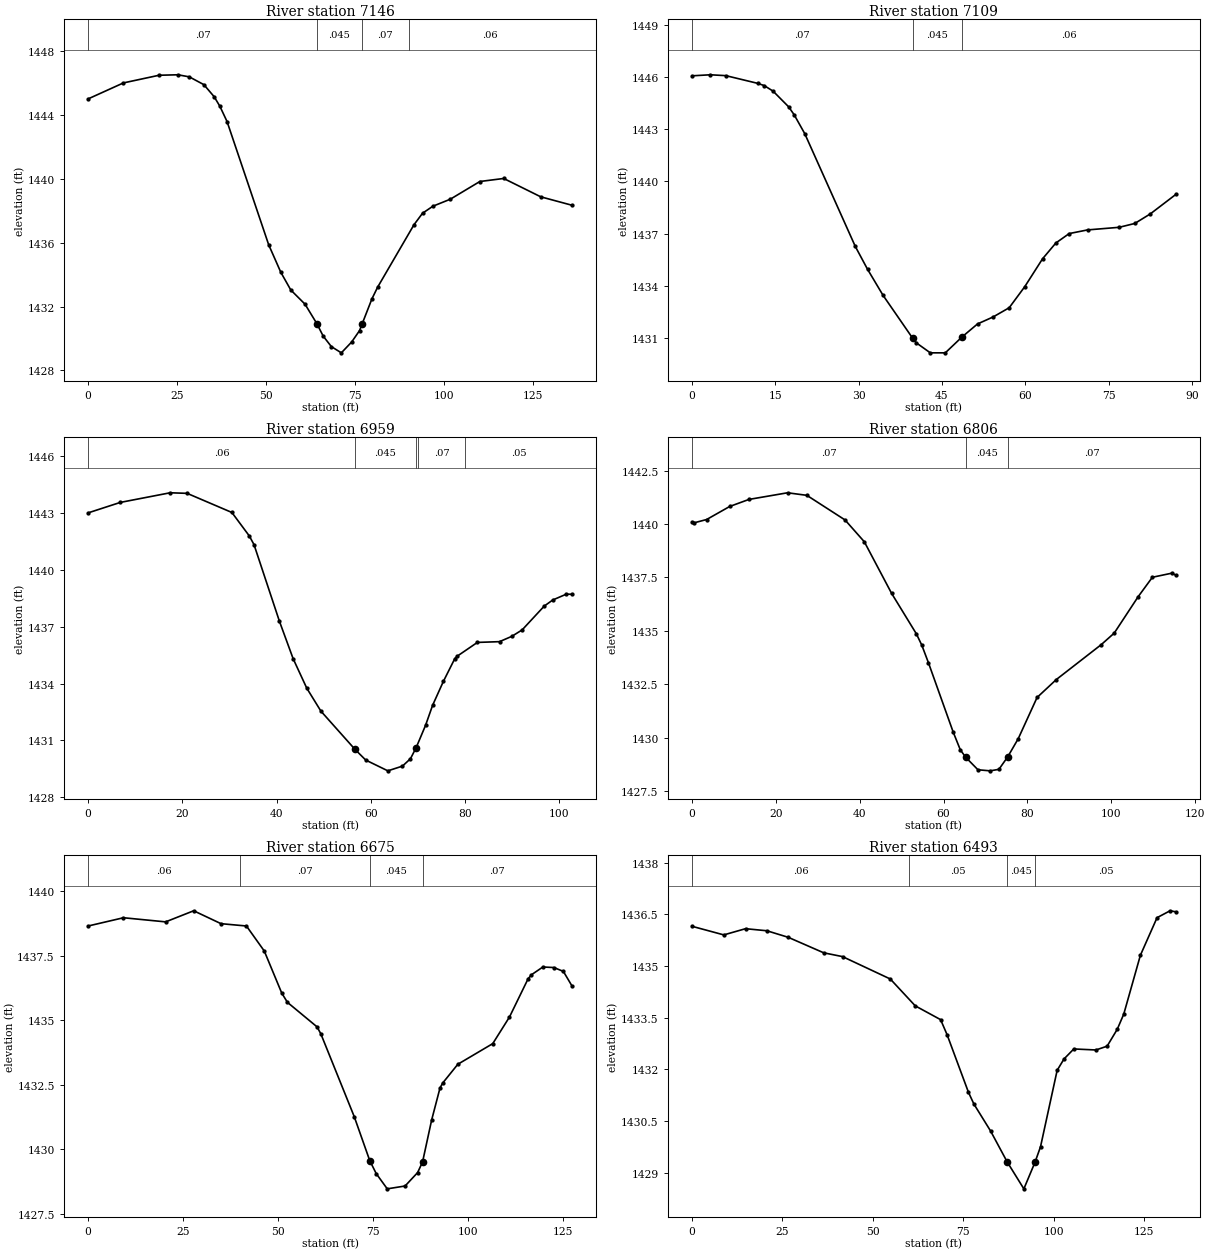
Type RM Length L Ch R = 1 ,7146    ,37.5,37.5,37.5
XS GIS Cut Line= 2
2169816.31037692696288.9808086682169732.10198002696182.255148119
#Sta/Elev= 30
       0 1445.02     9.9 1446.02    19.9  1446.5    25.2 1446.53    28.4  1446.4
    32.5 1445.91    35.4 1445.15      37 1444.55      39  1443.6    50.7 1435.87
    54.1 1434.15    56.9 1433.04    60.9 1432.15    64.21430.938      66 1430.15
    68.3 1429.49    71.1  1429.1      74 1429.78    76.2 1430.49    76.9 1430.89
    79.7 1432.49    81.3 1433.22    91.5 1437.13    93.9 1437.85    96.8 1438.29
   101.7 1438.73     110 1439.84   116.7 1440.03   127.1 1438.88   135.9 1438.35
#Mann= 4 ,-1,0
       0     .07       0    64.2    .045       0    76.9     .07       0
      90     .06       0
Bank Sta=64.2,76.9
XS Rating Curve= 0 ,0
Exp/Cntr(USF)=0,0
Exp/Cntr=0.3,0.1

Type RM Length L Ch R = 1 ,7109    ,149.4,149.4,149.4
XS GIS Cut Line= 2
2169835.38025244696246.6206335622169775.72010298696183.152389462
#Sta/Elev= 29
       0 1446.06     3.3 1446.12     6.1 1446.07    11.8 1445.63      13  1445.5
    14.6 1445.18    17.4 1444.28    18.4 1443.82    20.3 1442.74    29.4 1436.26
    31.6 1434.95    34.4 1433.45    39.7    1431    40.4 1430.72    42.9 1430.15
    45.6 1430.15    48.6 1431.06    51.4 1431.81    54.2 1432.21    57.1 1432.74
    59.9 1433.95    63.1 1435.55    65.5 1436.46    67.9    1437    71.2 1437.21
    76.9 1437.36    79.7 1437.58    82.5 1438.13    87.1 1439.25
#Mann= 3 ,-1,0
       0     .07       0    39.7    .045       0    48.6     .06       0
Bank Sta=39.7,48.6
XS Rating Curve= 0 ,0
Exp/Cntr(USF)=0,0
Exp/Cntr=0.3,0.1

Type RM Length L Ch R = 1 ,6959    ,153.1,153.1,153.1
XS GIS Cut Line= 2
2169958.50864599696178.9211731892169903.50283444696092.181239586
#Sta/Elev= 30
       0 1443.01     6.8 1443.56    17.4 1444.07      21 1444.04    30.5 1443.03
    34.2 1441.79    35.2 1441.33    40.6 1437.28    43.5 1435.31    46.4 1433.75
    49.4 1432.54    56.6 1430.53    58.9 1429.96    63.6 1429.39    66.7 1429.64
    68.4 1430.03    69.6 1430.61    71.6 1431.79    73.1 1432.85    75.4 1434.12
    77.8 1435.31    78.3 1435.44    82.6 1436.17    87.3 1436.21    89.9 1436.49
    92.1 1436.83    96.8 1438.09    98.6 1438.41   101.5 1438.72   102.7 1438.71
#Mann= 5 ,-1,0
       0     .06       0    56.6    .045       0    69.6     .06       0
      70     .07       0      80     .05       0
Bank Sta=56.6,69.6
XS Rating Curve= 0 ,0
Exp/Cntr(USF)=0,0
Exp/Cntr=0.3,0.1

Type RM Length L Ch R = 1 ,6806    ,131.5,131.5,131.5
XS GIS Cut Line= 2
2170093.10029719696113.0556841352170036.82512076696012.352736829
#Sta/Elev= 29
       0 1440.09      .6 1440.06     3.5 1440.21       9 1440.82    13.6 1441.15
    22.8 1441.46    27.4 1441.34    36.5 1440.19    41.1 1439.17    47.6 1436.76
    53.5 1434.87    54.8 1434.34    56.4 1433.51    62.3 1430.27      64 1429.44
    65.3 1429.09    68.2 1428.51    71.1 1428.46    73.2 1428.53    75.31429.115
    77.8 1429.96    82.3 1431.89    86.9 1432.73    97.6 1434.36   100.7  1434.9
   106.4  1436.6   109.8 1437.51   114.4  1437.7   115.4 1437.61
#Mann= 3 ,-1,0
       0     .07       0    65.3    .045       0    75.3     .07       0
Bank Sta=65.3,75.3
XS Rating Curve= 0 ,0
Exp/Cntr(USF)=0,0
Exp/Cntr=0.3,0.1

Type RM Length L Ch R = 1 ,6675    ,181.4,181.4,181.4
XS GIS Cut Line= 2
2170212.00951826696053.1968397052170147.60100388695943.185216598
#Sta/Elev= 30
       0 1438.66     9.3 1438.98    20.4 1438.82    27.8 1439.25      35 1438.75
    41.7 1438.66    46.4 1437.69      51 1436.06    52.5  1435.7    60.3 1434.75
    61.3 1434.48    70.1 1431.27    74.2 1429.56    75.9 1429.06    78.8 1428.47
    83.5 1428.58    86.8  1429.1    88.1 1429.51    90.5 1431.14    92.7 1432.38
    93.4 1432.57    97.4  1433.3   106.6  1434.1     111 1435.13   115.9 1436.61
   116.8 1436.77   119.8 1437.07   122.7 1437.05   125.2  1436.9   127.5 1436.33
#Mann= 4 ,-1,0
       0     .06       0      40     .07       0    74.2    .045       0
    88.1     .07       0
Bank Sta=74.2,88.1
XS Rating Curve= 0 ,0
Exp/Cntr(USF)=0,0
Exp/Cntr=0.3,0.1

Type RM Length L Ch R = 1 ,6493    ,46.5,46.5,46.5
XS GIS Cut Line= 2
2170372.79573665695972.803730512 2170306.5066817695856.680350565
#Sta/Elev= 29
       0 1436.15     8.8  1435.9    14.8 1436.08    20.7 1436.02    26.6 1435.83
    36.4 1435.38    41.6 1435.27    54.8 1434.62    61.7 1433.84    68.7 1433.44
    70.5    1433    76.4 1431.33    77.9 1430.99    82.5 1430.21    87.1 1429.31
    91.7 1428.53    94.81429.307    96.3 1429.75   100.9 1431.97   102.8  1432.3
   105.5 1432.59   111.6 1432.56   114.7 1432.67   117.5 1433.16   119.3  1433.6
   123.9 1435.31   128.5  1436.4   132.1  1436.6   133.7 1436.57
#Mann= 4 ,-1,0
       0     .06       0      60     .05       0    87.1    .045       0
    94.8     .05       0
Bank Sta=87.1,94.8
XS Rating Curve= 0 ,0
Exp/Cntr(USF)=0,0
Exp/Cntr=0.3,0.1