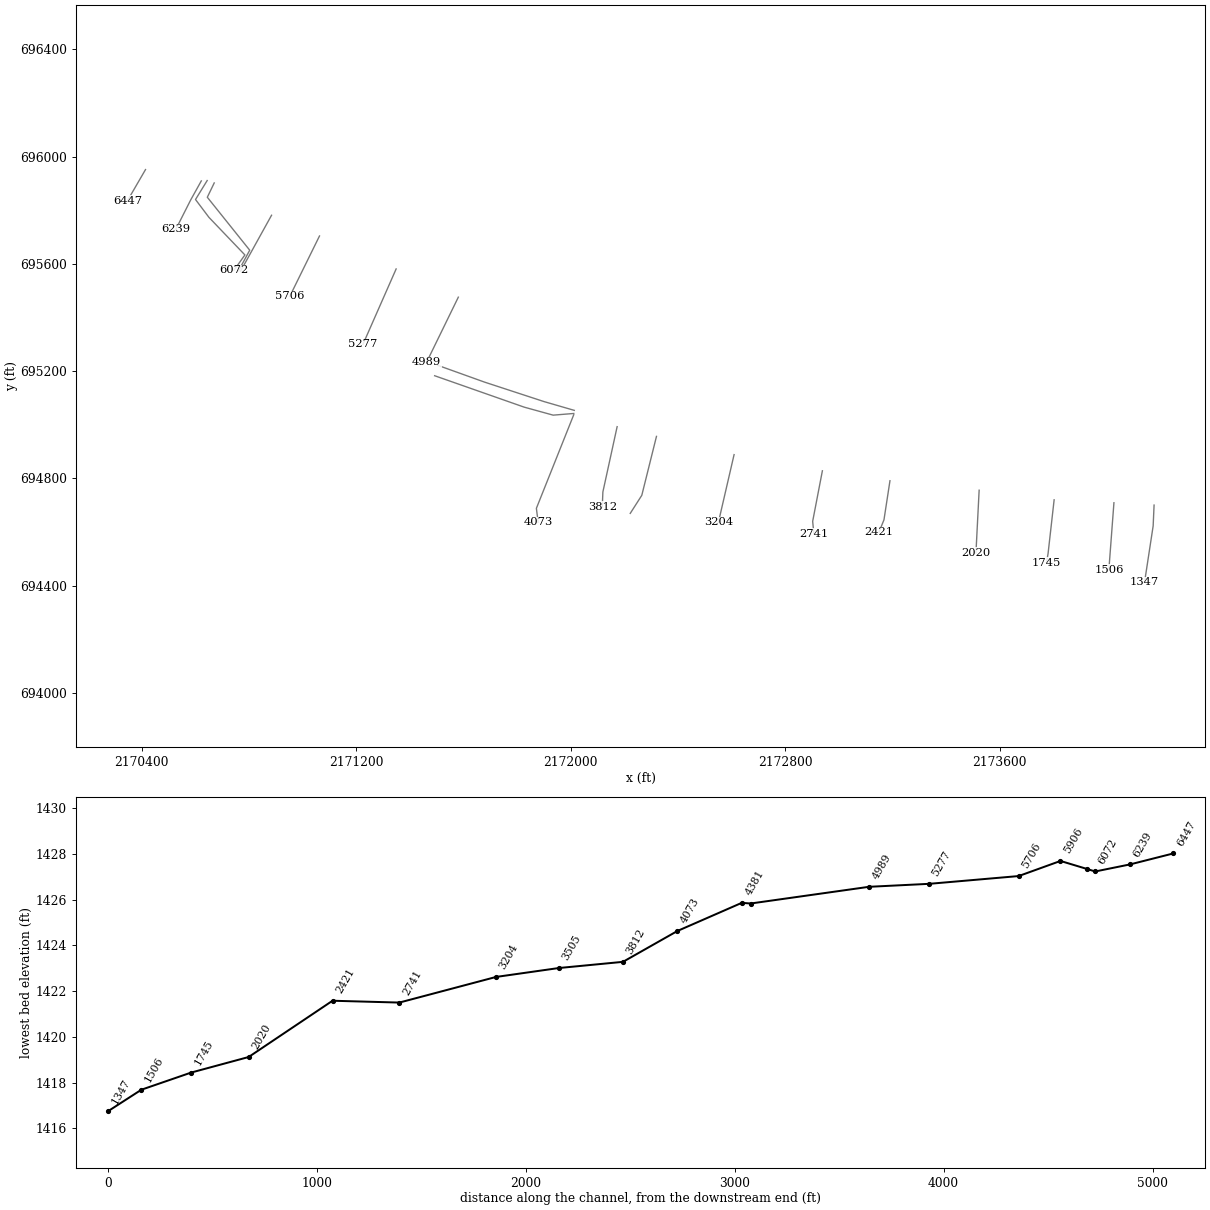
HEC-RAS study BULLRN.prj: BULLRN

--- BULLRN.g01 (geometry) --- (continued)

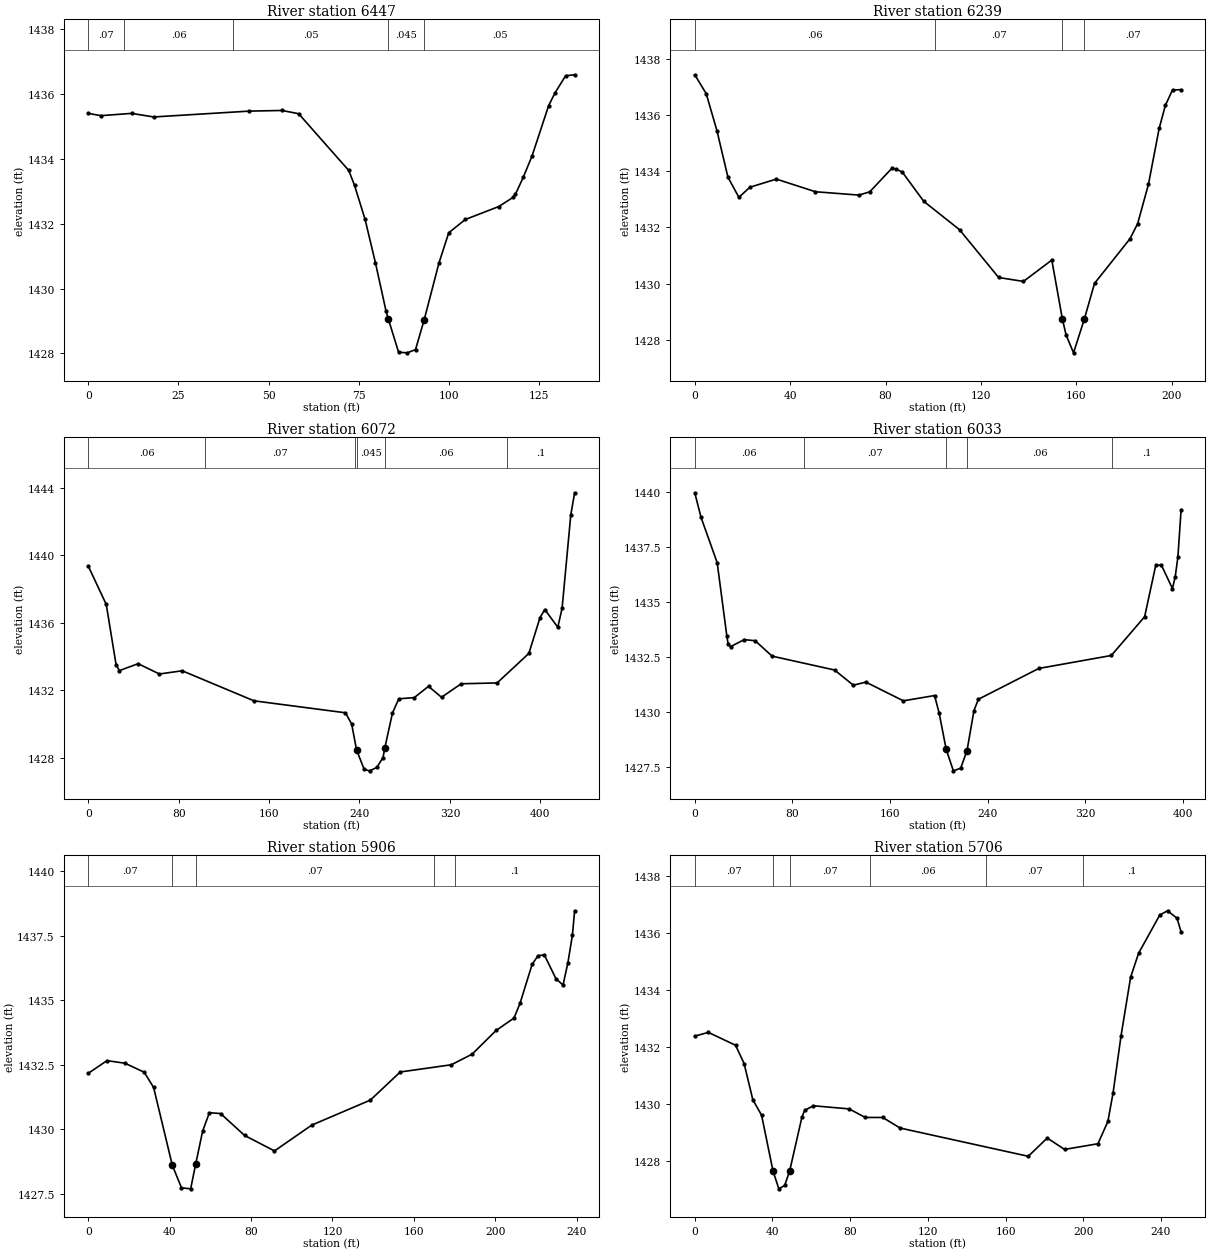
Type RM Length L Ch R = 1 ,6447    ,207.4,207.4,207.4
XS GIS Cut Line= 2
2170414.55599498695951.5991468282170346.93343223695835.005776317
#Sta/Elev= 29
       0  1435.4     3.5 1435.33      12  1435.4    18.1 1435.29    44.6 1435.47
    53.7 1435.49    58.3 1435.39    72.2 1433.64    73.8 1433.18    76.7 1432.14
    79.6 1430.79    82.5 1429.32    83.21429.051      86 1428.04    88.4 1428.02
    90.7 1428.12    93.11429.039    97.2 1430.79    99.9 1431.72   104.5 1432.13
   113.8 1432.53   117.7 1432.81   118.4 1432.91   120.6 1433.44     123 1434.09
   127.6 1435.64   129.4 1436.04   132.3 1436.56   134.8 1436.59
#Mann= 5 ,-1,0
       0     .07       0      10     .06       0      40     .05       0
    83.2    .045       0    93.1     .05       0
Bank Sta=83.2,93.1
XS Rating Curve= 0 ,0
Exp/Cntr(USF)=0,0
Exp/Cntr=0.3,0.1

Type RM Length L Ch R = 1 ,6239    ,167.2,167.2,167.2
XS GIS Cut Line= 3
2170622.55873811  695909.3431447 2170583.1831148695838.635715777
2170527.58394345695728.902808161
#Sta/Elev= 30
       0 1437.43     4.8 1436.76     9.3 1435.44    13.9 1433.79    18.5 1433.07
    23.1 1433.43    34.2 1433.72    50.6 1433.27    68.9 1433.15    73.4 1433.27
    82.6  1434.1    84.3 1434.08      87 1433.97      96 1432.93     111 1431.92
   127.4 1430.22   137.8 1430.08   149.7 1430.84   154.11428.755   155.7 1428.17
   158.8 1427.54   163.3 1428.73   167.6 1430.01   182.5  1431.6   185.7 1432.14
   190.2 1433.53   194.7 1435.52   197.3 1436.34   200.3 1436.89   203.9  1436.9
#Mann= 4 ,-1,0
       0     .06       0  100.93     .07       0   154.1    .045       0
   163.3     .07       0
Bank Sta=154.1,163.3
XS Rating Curve= 0 ,0
Exp/Cntr(USF)=0,0
Exp/Cntr=0.3,0.1

Type RM Length L Ch R = 1 ,6072    ,39.1,39.1,39.1
XS GIS Cut Line= 5
 2170644.4886802695910.7089964732170600.96232818695839.969156781
2170651.04154906695773.4486965992170785.09229357695633.290173237
2170744.45964147695576.169994637
#Sta/Elev= 30
       0 1439.36    15.9 1437.09    24.6 1433.52    27.5 1433.17    44.1 1433.58
    62.9 1432.97    83.1 1433.16   146.6 1431.38   227.6 1430.67   233.1    1430
   237.4 1428.47   244.2 1427.31     249 1427.23   255.3 1427.43   260.8 1428.01
   262.41428.585   269.2 1430.66   274.8  1431.5   288.5 1431.57   301.1 1432.24
   312.6 1431.59     330 1432.39   361.8 1432.44   389.9 1434.19   399.7  1436.3
     404 1436.79   415.5 1435.74   419.3 1436.86     427  1442.4   430.4 1443.71
#Mann= 6 ,-1,0
       0     .06       0  103.06     .07       0  236.32      .1       0
   237.4    .045       0   262.4     .06       0  370.27      .1       0
Bank Sta=237.4,262.4
XS Rating Curve= 0 ,0
Exp/Cntr(USF)=0,0
Exp/Cntr=0.3,0.1

Type RM Length L Ch R = 1 ,6033    ,127.2,127.2,127.2
XS GIS Cut Line= 4
2170670.74574071695901.751923286 2170644.9658813695848.414283138
2170803.09374712695650.931597716 2170761.8669008695574.919839292
#Sta/Elev= 30
       0 1439.97     5.1 1438.86    18.4 1436.79    26.3 1433.46    27.3 1433.12
    29.3 1432.98    40.6  1433.3    49.5 1433.25    63.4 1432.55   114.6 1431.92
     130 1431.23   140.3 1431.37     171 1430.52   196.6 1430.76   200.4 1429.95
   206.1 1428.32     212 1427.34     218 1427.46   223.2 1428.26   228.9 1430.08
   232.5 1430.59     282 1431.99   341.5 1432.58   368.8 1434.34   377.9 1436.67
   382.5 1436.69   391.6 1435.62   393.9 1436.16   396.1 1437.07   398.7  1439.2
#Mann= 5 ,-1,0
       0     .06       0   89.24     .07       0   206.1    .045       0
   223.2     .06       0  342.23      .1       0
Bank Sta=206.1,223.2
XS Rating Curve= 0 ,0
Exp/Cntr(USF)=0,0
Exp/Cntr=0.3,0.1

Type RM Length L Ch R = 1 ,5906    ,200.1,200.1,200.1
XS GIS Cut Line= 2
2170884.49878392695781.2652492432170768.71440048 695572.19486965
#Sta/Elev= 30
       0 1432.17     9.2 1432.66      18 1432.56    27.5 1432.21    32.1 1431.62
    41.3  1428.6    45.8 1427.73    50.3 1427.69    52.8 1428.66    56.2 1429.93
    59.5 1430.64      65 1430.61    76.8 1429.76    91.5 1429.16   109.8 1430.16
   138.6 1431.13   153.3 1432.22   178.4  1432.5   188.6 1432.91   200.4 1433.83
   209.2 1434.31   212.2 1434.89   218.1 1436.39     221 1436.73   224.1 1436.76
   229.8 1435.84   233.3 1435.59   235.7 1436.46   237.9 1437.52     239 1438.47
#Mann= 5 ,-1,0
       0     .07       0    41.3    .045       0    52.8     .07       0
     170     .06       0     180      .1       0
Bank Sta=41.3,52.8
XS Rating Curve= 0 ,0
Exp/Cntr(USF)=0,0
Exp/Cntr=0.3,0.1

Type RM Length L Ch R = 1 ,5706    ,428.4,428.4,428.4
XS GIS Cut Line= 2
2171063.27528231695703.9996056312170952.69500588 695479.30048393
#Sta/Elev= 30
       0 1432.38       7 1432.51      21 1432.06    25.4 1431.42    29.9 1430.15
    34.4 1429.61    40.3 1427.65    43.3 1427.03    46.3 1427.15    48.91427.668
    55.2 1429.55    56.6 1429.78    61.1 1429.94    79.5 1429.83    87.8 1429.53
    96.8 1429.53   105.7 1429.16   171.7 1428.17   181.5 1428.81   190.4 1428.41
   207.6 1428.61   212.7 1429.39   215.4  1430.4   219.5  1432.4   224.4 1434.44
   228.5 1435.28   239.4 1436.62   243.4 1436.77   248.3 1436.51   250.4 1436.03
#Mann= 6 ,-1,0
       0     .07       0    40.3    .045       0    48.9     .07       0
      90     .06       0     150     .07       0     200      .1       0
Bank Sta=40.3,48.9
XS Rating Curve= 0 ,0
Exp/Cntr(USF)=0,0
Exp/Cntr=0.3,0.1

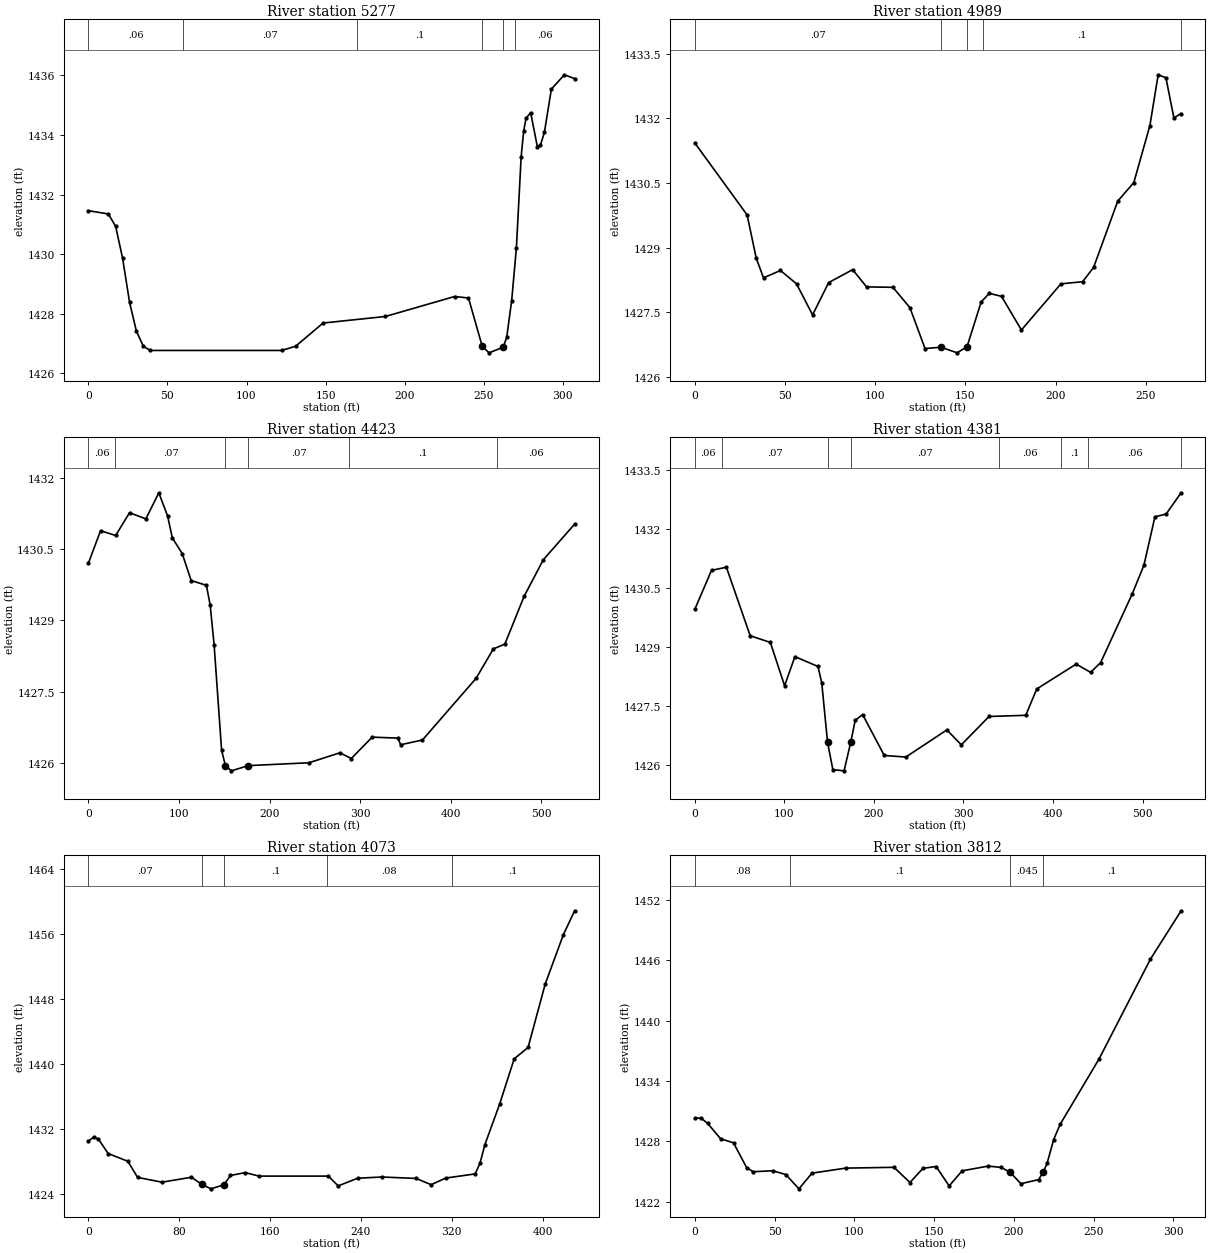
Type RM Length L Ch R = 1 ,5277    ,288.1,288.1,288.1
XS GIS Cut Line= 2
 2171349.0147166695581.034338243  2171225.164807695299.718115011
#Sta/Elev= 30
       0 1431.46    12.7 1431.35    17.3 1430.93    21.7 1429.86    26.1 1428.38
    30.4 1427.42    34.8 1426.91    39.2 1426.77   122.2 1426.77     131 1426.91
   148.4 1427.69   187.8 1427.91   231.5 1428.58   240.3 1428.53     249 1426.91
   253.3 1426.69   262.3 1426.88   264.5 1427.22   267.6 1428.44   270.6 1430.22
   273.6 1433.27   275.2 1434.14   276.7 1434.56   279.6 1434.75   283.9 1433.59
   285.8 1433.66   288.3 1434.09   292.7 1435.54   300.9 1436.02   307.4 1435.89
#Mann= 6 ,-1,0
       0     .06       0      60     .07       0     170      .1       0
     249    .045       0   262.3      .1       0     270     .06       0
Bank Sta=249,262.3
XS Rating Curve= 0 ,0
Exp/Cntr(USF)=0,0
Exp/Cntr=0.3,0.1

Type RM Length L Ch R = 1 ,4989    ,566.7,566.7,566.7
XS GIS Cut Line= 2
2171580.88752679695475.8296433042171462.75608939695233.631732993
#Sta/Elev= 30
       0 1431.43      29 1429.76    34.1 1428.75    38.1  1428.3    47.5 1428.47
    56.4 1428.16    65.3 1427.44    74.2 1428.19    87.5 1428.49    95.2 1428.09
   109.8 1428.08   119.2 1427.61   127.6 1426.66   136.5 1426.69   145.4 1426.56
   150.91426.704   158.7 1427.74   163.2 1427.94     170 1427.87     181 1427.09
   202.9 1428.16   214.9 1428.21     221 1428.54   234.4 1430.08   243.3 1430.51
   252.2 1431.83   256.8 1433.01   261.1 1432.94   265.5 1432.01   269.5 1432.11
#Mann= 5 ,-1,0
       0     .07       0   136.5    .045       0   150.9     .07       0
     160      .1       0  269.47     .07       0
Bank Sta=136.5,150.9
XS Rating Curve= 0 ,0
Exp/Cntr(USF)=0,0
Exp/Cntr=0.3,0.1

Type RM Length L Ch R = 1 ,4423    ,42.1,42.1,42.1
XS GIS Cut Line= 4
2172013.18739709695053.8015487342171900.21203987695086.571643813
2171678.87455858695159.0238409282171503.71540072 695221.92190216
#Sta/Elev= 30
       0  1430.2    13.5 1430.89    30.2 1430.79    45.5 1431.27    63.5 1431.14
    77.8 1431.69    87.5  1431.2    92.7 1430.74   103.6 1430.41   113.5 1429.84
   130.3 1429.74   134.5 1429.32   138.8 1428.49   147.1 1426.26   151.3 1425.94
   157.8 1425.83   176.6 1425.94   243.4    1426   277.6 1426.21   290.2 1426.09
   313.2 1426.54   341.7 1426.52   344.6 1426.38   368.7 1426.48   427.9 1427.78
   446.9  1428.4   459.6  1428.5   480.9 1429.51   502.1 1430.28   536.6 1431.03
#Mann= 6 ,-1,0
       0     .06       0      30     .07       0   151.3    .045       0
   176.6     .07       0  287.63      .1       0  450.53     .06       0
Bank Sta=151.3,176.6
XS Rating Curve= 0 ,0
Exp/Cntr(USF)=0,0
Exp/Cntr=0.3,0.1

Type RM Length L Ch R = 1 ,4381    ,308,308,308
XS GIS Cut Line= 4
2172011.33896727695042.1986440382171934.45163607 695035.94693082
2171826.16748678695065.8710160662171492.56890885695182.909180637
#Sta/Elev= 30
       0 1429.96    18.7 1430.95    35.3 1431.03    61.9 1429.29    84.4 1429.12
   100.3 1428.02   111.8 1428.76   137.6 1428.51   141.8 1428.09   148.3 1426.58
   154.2 1425.89   166.7 1425.86   174.3  1426.6   179.1 1427.14   187.4 1427.29
   211.6 1426.25   235.7 1426.21   281.5  1426.9   297.6 1426.52   328.6 1427.24
   369.6 1427.27   381.9 1427.94   425.9 1428.57     442 1428.36   453.2 1428.61
   488.6 1430.36   501.5 1431.08   513.8 1432.31   526.3 1432.38     543 1432.92
#Mann= 8 ,-1,0
       0     .06       0      30     .07       0   148.3    .045       0
   174.3     .07       0  339.48     .06       0  409.48      .1       0
  439.48     .06       0  543.02     .07       0
Bank Sta=148.3,174.3
XS Rating Curve= 0 ,0
Exp/Cntr(USF)=0,0
Exp/Cntr=0.3,0.1

Type RM Length L Ch R = 1 ,4073    ,260.9,260.9,260.9
XS GIS Cut Line= 3
 2172011.2319766695037.4703134832171871.94278731 694688.52925851
2171878.44787304694636.488572618
#Sta/Elev= 30
       0 1430.51     4.6 1430.99     8.9 1430.77    17.5 1428.98    34.8 1428.03
    43.4 1426.04    64.9 1425.45    90.8 1426.06   100.21425.169     108 1424.63
   119.5 1425.14   125.2 1426.28   138.1 1426.63   150.3  1426.2   211.4  1426.2
     220 1424.99   237.2 1425.94   258.7 1426.09   288.8 1425.91   301.8 1425.14
   314.7 1425.96   340.6 1426.47   344.9 1427.79   349.2 1430.09   362.1 1435.05
     375 1440.66   387.2 1442.06   402.3 1449.88   418.3 1455.97   428.2 1458.91
#Mann= 5 ,-1,0
       0     .07       0   100.2    .045       0   119.5      .1       0
     210     .08       0     320      .1       0
Bank Sta=100.2,119.5
XS Rating Curve= 0 ,0
Exp/Cntr(USF)=0,0
Exp/Cntr=0.3,0.1

Type RM Length L Ch R = 1 ,3812    ,307,307,307
XS GIS Cut Line= 3
2172173.01344004694992.9658477052172119.85252832 694749.58190133
2172117.62186981694693.808679963
#Sta/Elev= 30
       0 1430.31     3.9 1430.31       8  1429.8    16.2 1428.26    24.3 1427.85
    32.5  1425.4    36.6 1424.98    48.9 1425.08    57.1  1424.7    65.3 1423.28
    73.5 1424.84    94.6 1425.34   124.9 1425.42   134.9 1423.91   143.1 1425.32
   151.3  1425.5   159.5 1423.57   167.6 1425.07     184 1425.54   192.1 1425.41
   197.7 1424.92   204.5 1423.79   215.6  1424.2   218.41424.924   220.9 1425.82
     225 1428.18   229.1  1429.7   253.5  1436.2   285.6 1446.09   304.9 1450.92
#Mann= 4 ,-1,0
       0     .08       0      60      .1       0   197.7    .045       0
   218.4      .1       0
Bank Sta=197.7,218.4
XS Rating Curve= 0 ,0
Exp/Cntr(USF)=0,0
Exp/Cntr=0.3,0.1

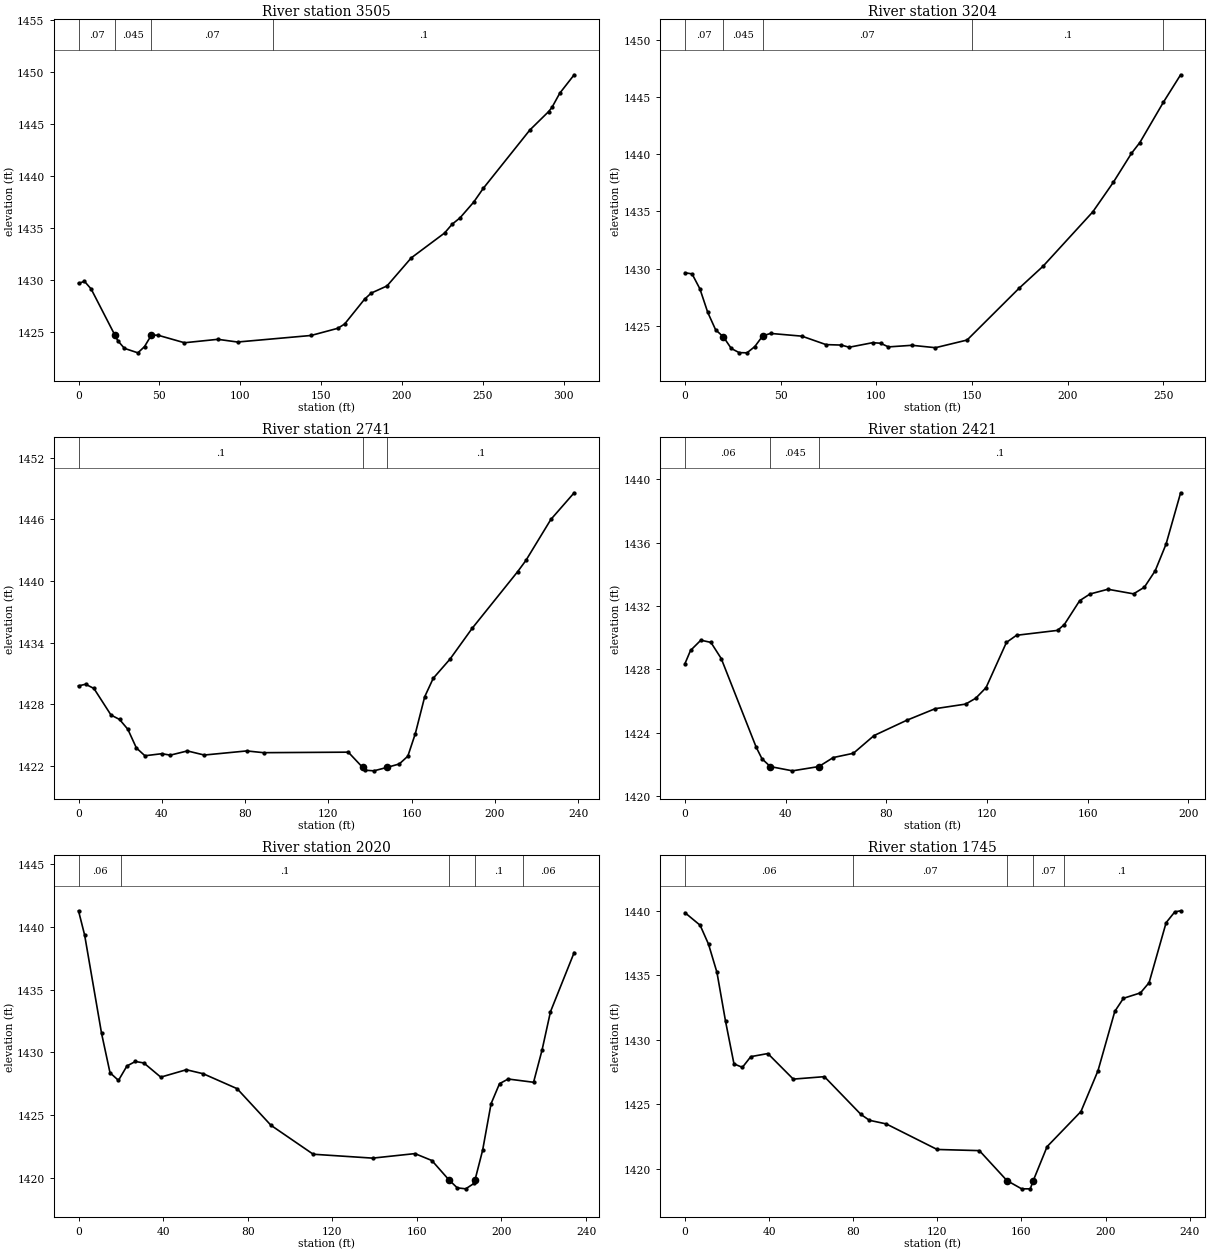
Type RM Length L Ch R = 1 ,3505    ,300.5,300.5,300.5
XS GIS Cut Line= 3
2172319.70320079 694956.759005222172264.97085274 694737.02468771
 2172221.9167187694669.701192031
#Sta/Elev= 30
       0 1429.69     3.7 1429.88     7.8 1429.15    22.31424.768    24.3 1424.17
    28.4 1423.44    36.7 1423.01    40.8 1423.61      451424.703      49 1424.71
    65.5 1423.98    86.1 1424.31    98.3 1424.05   143.8 1424.68   160.3 1425.37
   164.5 1425.78   176.8 1428.16   180.9 1428.75   190.7 1429.44   205.7 1432.14
   226.3 1434.53     231 1435.38   235.8 1435.98   244.3  1437.5   250.2 1438.82
     279 1444.43   290.6  1446.2   292.7 1446.61   297.5 1447.97   306.4 1449.74
#Mann= 4 ,-1,0
       0     .07       0    22.3    .045       0      45     .07       0
     120      .1       0
Bank Sta=22.3,45
XS Rating Curve= 0 ,0
Exp/Cntr(USF)=0,0
Exp/Cntr=0.3,0.1

Type RM Length L Ch R = 1 ,3204    ,462.9,462.9,462.9
XS GIS Cut Line= 2
2172609.05989866694888.7535140162172550.66162344694636.440359801
#Sta/Elev= 30
       0 1429.63     3.7 1429.53     7.8 1428.22    11.9 1426.16      16 1424.64
    20.1 1424.01    24.2    1423    28.3 1422.64    32.4 1422.62    36.5 1423.17
    40.6  1424.1    44.7 1424.32    61.1 1424.08    73.7 1423.34    81.7  1423.3
    85.8 1423.11    98.1 1423.51   102.2 1423.46   106.3 1423.14   118.6 1423.28
   130.9 1423.07   147.4 1423.74   174.5 1428.26   187.1  1430.2   213.1 1434.96
   223.8 1437.54   233.3 1440.08   237.7 1441.03     250 1444.56     259 1446.96
#Mann= 5 ,-1,0
       0     .07       0    20.1    .045       0    40.6     .07       0
     150      .1       0     250     .03       0
Bank Sta=20.1,40.6
XS Rating Curve= 0 ,0
Exp/Cntr(USF)=0,0
Exp/Cntr=0.3,0.1

Type RM Length L Ch R = 1 ,2741    ,319.9,319.9,319.9
XS GIS Cut Line= 3
2172938.31690477694828.4919413122172902.07709161694640.023743014
2172906.50030267694594.022348021
#Sta/Elev= 30
       0 1429.78     3.4 1429.94     7.4 1429.53    15.6 1426.94    19.7 1426.51
    23.7 1425.55    27.8 1423.73    31.9 1422.97      40 1423.17    44.1 1423.03
    52.3 1423.44    60.4 1423.04    80.8 1423.44    88.9 1423.27   129.6 1423.32
   136.51421.832   137.8 1421.56   141.9  1421.5   148.1 1421.83   154.1 1422.17
   158.2 1422.93   161.8 1425.13   166.3 1428.72   170.4 1430.52   178.5  1432.4
   189.1 1435.39   210.9  1440.9   214.9    1442   226.9    1446   238.1  1448.6
#Mann= 3 ,-1,0
       0      .1       0   136.5    .045       0   148.1      .1       0
Bank Sta=136.5,148.1
XS Rating Curve= 0 ,0
Exp/Cntr(USF)=0,0
Exp/Cntr=0.3,0.1

Type RM Length L Ch R = 1 ,2421    ,401.6,401.6,401.6
XS GIS Cut Line= 3
2173190.27496459694791.3877072782173167.96691452694645.847063334
2173149.38942808 694599.84566834
#Sta/Elev= 30
       0 1428.36     2.2 1429.19     6.3 1429.84    10.3  1429.7    14.4 1428.68
    28.3 1423.07    30.6 1422.34    33.91421.849    42.7 1421.58    53.21421.852
    58.9 1422.42    66.9 1422.69    75.1 1423.81      88 1424.77    99.4 1425.51
   111.5  1425.8   115.5 1426.17   119.6 1426.84   127.7  1429.7   131.7 1430.15
     148 1430.46   150.7 1430.83   156.8 1432.34   160.9 1432.76     168 1433.06
   178.2 1432.77   182.5 1433.19   186.8 1434.23   191.1 1435.91   196.9 1439.16
#Mann= 3 ,-1,0
       0     .06       0    33.9    .045       0    53.2      .1       0
Bank Sta=33.9,53.2
XS Rating Curve= 0 ,0
Exp/Cntr(USF)=0,0
Exp/Cntr=0.3,0.1

Type RM Length L Ch R = 1 ,2020    ,275.3,275.3,275.3
XS GIS Cut Line= 2
2173522.77204088694756.0678765022173510.82937103694521.991547361
#Sta/Elev= 30
       0  1441.3     2.9 1439.36    10.9 1431.52    14.9 1428.38    18.9 1427.77
    22.9 1428.92    26.9 1429.28    30.9 1429.16    38.9 1428.03      51 1428.62
      59  1428.3      75 1427.11      91 1424.19     111 1421.88   139.1 1421.57
   159.1 1421.93   167.1 1421.38   175.1 1419.85   179.1  1419.2   183.1 1419.12
   187.1 1419.56   187.51419.823   191.1 1422.19   195.1 1425.91   199.1 1427.51
   203.2 1427.88   215.2 1427.62   219.2 1430.18   223.2 1433.25   234.4 1437.97
#Mann= 5 ,-1,0
       0     .06       0      20      .1       0   175.1    .045       0
   187.5      .1       0     210     .06       0
Bank Sta=175.1,187.5
XS Rating Curve= 0 ,0
Exp/Cntr(USF)=0,0
Exp/Cntr=0.3,0.1

Type RM Length L Ch R = 1 ,1745    ,238.2,238.2,238.2
XS GIS Cut Line= 3
2173802.37485467694720.3105346452173779.76733149694519.791633391
2173773.86971674694486.371816515
#Sta/Elev= 30
       0 1439.83     7.2 1438.86    11.2 1437.39    15.2 1435.21    19.3 1431.41
    23.3 1428.12    27.3 1427.85    31.3 1428.68    39.4 1428.92    51.5 1426.94
    66.3 1427.13    83.7  1424.2    87.7 1423.75    95.7 1423.47   119.9 1421.49
     140  1421.4   153.1 1419.08   160.1 1418.44   164.2 1418.44   165.6 1419.07
   172.2 1421.71   188.3 1424.43   196.4 1427.59   204.4 1432.19   208.5  1433.2
   216.6 1433.62   220.7 1434.41   228.8 1439.06   232.9 1439.89   235.7 1439.98
#Mann= 5 ,-1,0
       0     .06       0      80     .07       0   153.1    .045       0
   165.6     .07       0     180      .1       0
Bank Sta=153.1,165.6
XS Rating Curve= 0 ,0
Exp/Cntr(USF)=0,0
Exp/Cntr=0.3,0.1

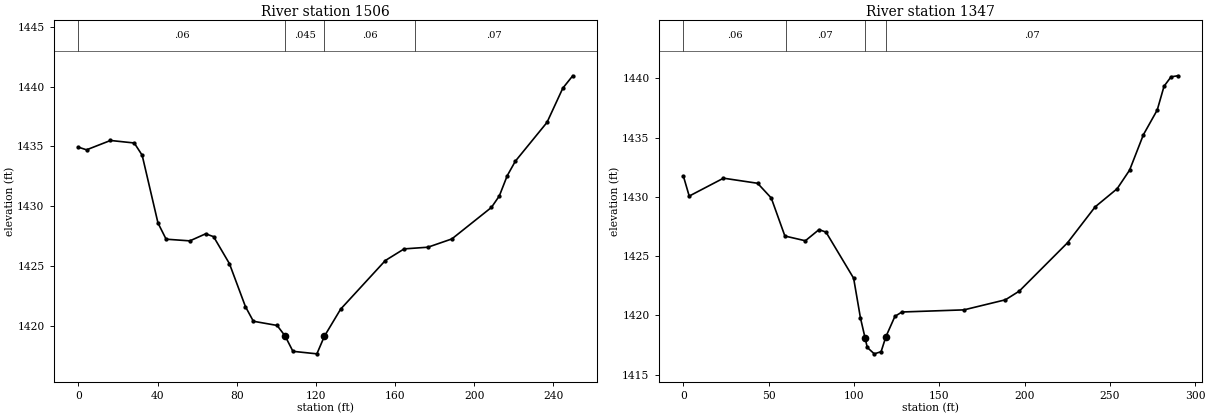
Type RM Length L Ch R = 1 ,1506    ,159.7,159.7,159.7
XS GIS Cut Line= 2
 2174025.3556338694709.3062673842174006.50881099694460.217447941
#Sta/Elev= 30
       0 1434.94     4.1 1434.72    16.2  1435.5    28.2 1435.29    32.2 1434.27
    40.2 1428.61    44.3 1427.26    56.3 1427.12    64.3 1427.71    68.3 1427.47
    76.3 1425.22    84.4 1421.63    88.4 1420.41   100.4 1420.06   104.4 1419.19
   108.4  1417.9   120.5 1417.69   124.3 1419.16   132.5 1421.42   155.1 1425.48
   164.6 1426.45   176.6 1426.59   188.7 1427.28   208.7 1429.91   212.7 1430.87
   216.7 1432.56   220.8 1433.77   236.8 1437.01   244.8 1439.87   249.8  1440.9
#Mann= 4 ,-1,0
       0     .06       0   104.4    .045       0   124.3     .06       0
     170     .07       0
Bank Sta=104.4,124.3
XS Rating Curve= 0 ,0
Exp/Cntr(USF)=0,0
Exp/Cntr=0.3,0.1

Type RM Length L Ch R = 1 ,1347    ,260.9,260.9,260.9
XS GIS Cut Line= 3
2174175.03738604694700.6079392482174171.57765262 694622.79907087
2174139.56647393694413.297618247
#Sta/Elev= 30
       0 1431.74     3.4 1430.06    23.5 1431.57    43.5 1431.14    51.5  1429.9
    59.5 1426.69    71.5 1426.29    79.5 1427.23    83.6 1427.02    99.8 1423.13
   103.8 1419.78   106.51418.099   107.8 1417.29   111.9 1416.75   115.9 1416.93
   118.7 1418.19     124 1419.91   128.1 1420.28   164.5 1420.46   188.8 1421.31
   196.9 1422.04   225.2 1426.12   241.4 1429.15   254.3 1430.68   261.6 1432.25
   269.7 1435.24   277.8 1437.32   281.8 1439.33   285.9 1440.12   289.8 1440.21
#Mann= 4 ,-1,0
       0     .06       0      60     .07       0   106.5    .045       0
   118.7     .07       0
Bank Sta=106.5,118.7
XS Rating Curve= 0 ,0
Exp/Cntr(USF)=0,0
Exp/Cntr=0.3,0.1