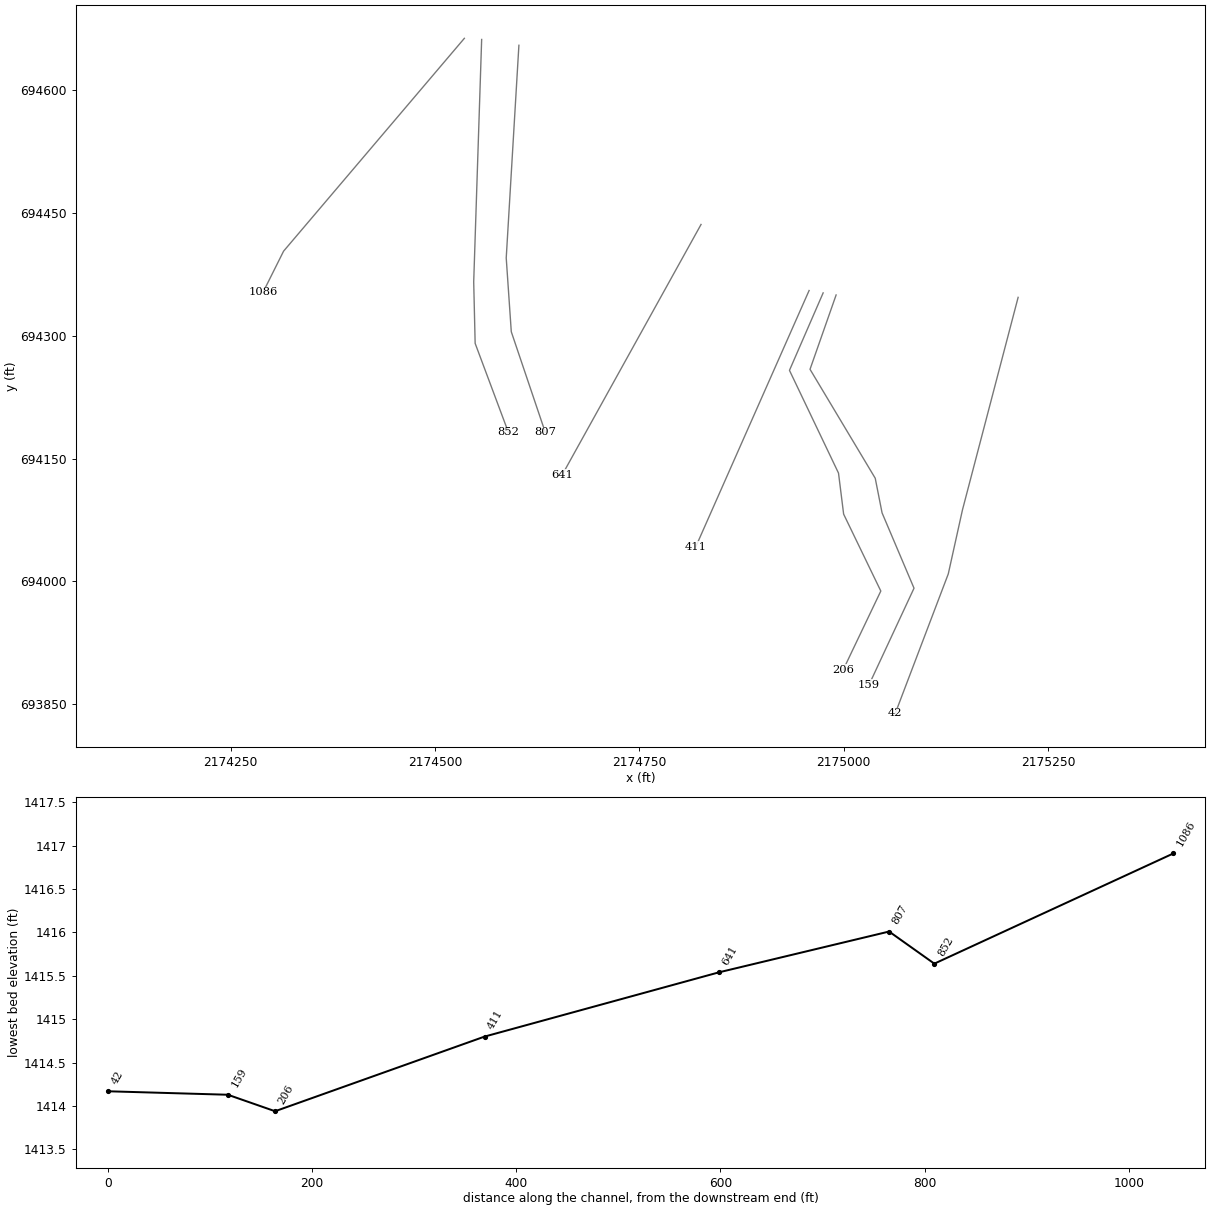
HEC-RAS study BULLRN.prj: BULLRN

--- BULLRN.g01 (geometry) --- (continued)

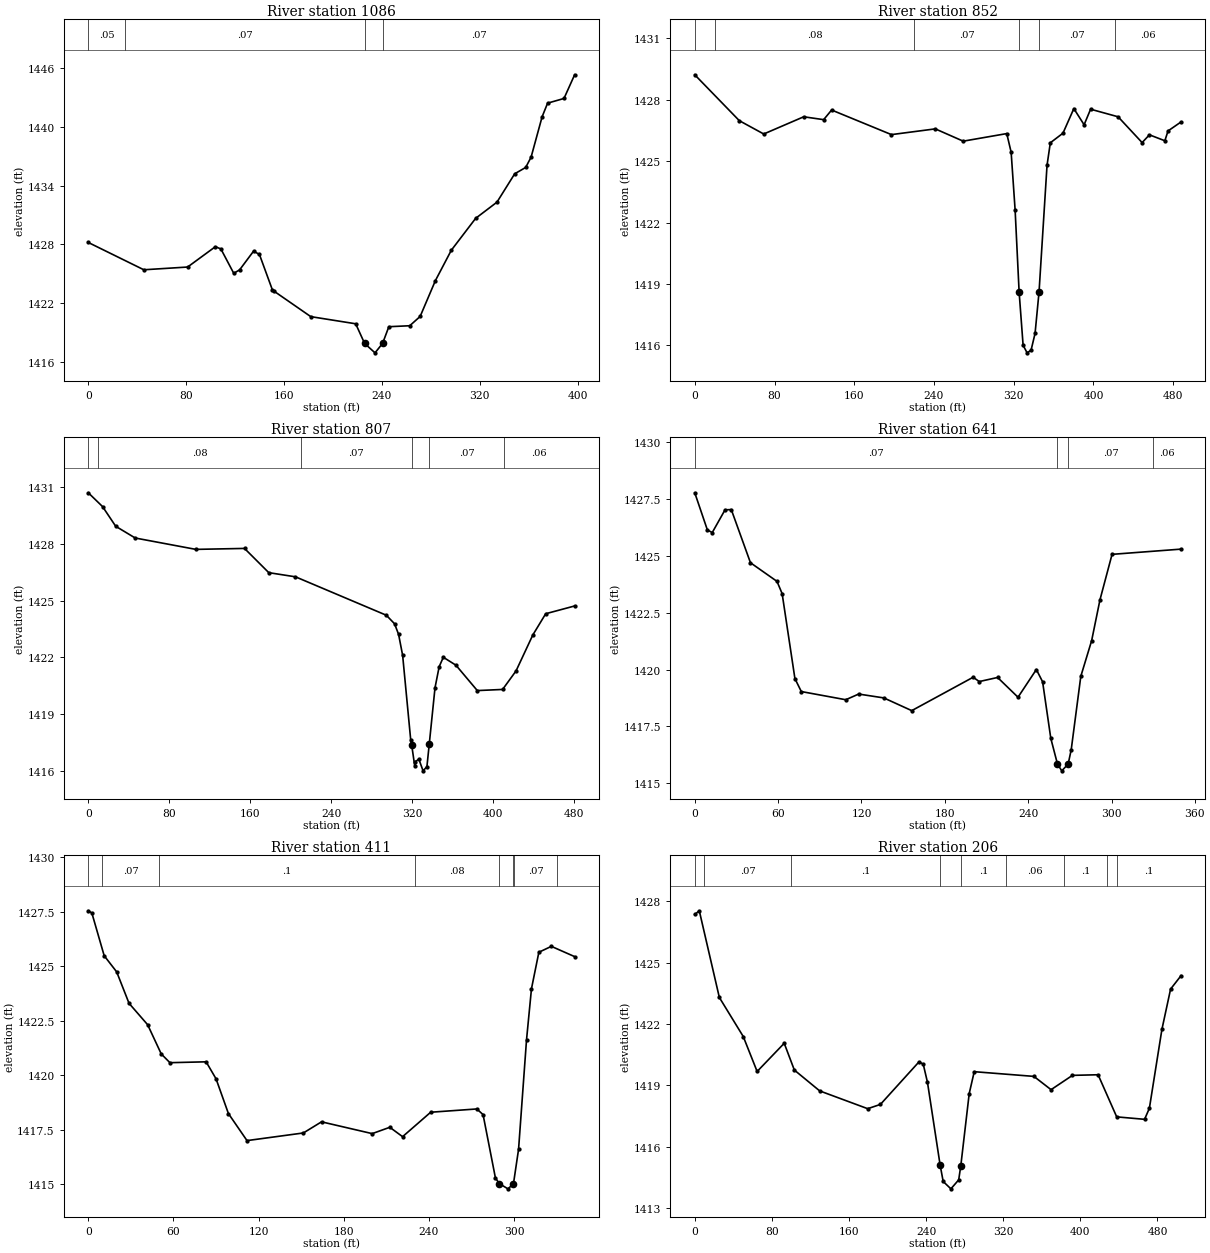
Type RM Length L Ch R = 1 ,1086    ,234.2,234.2,234.2
XS GIS Cut Line= 3
2174535.98483311694663.7602947362174314.81191807694403.556865276
2174289.72087309694353.374775309
#Sta/Elev= 30
       0 1428.19    45.4  1425.4    81.2 1425.68   103.9 1427.76   108.4 1427.53
   118.9 1425.04   123.7 1425.39   135.1  1427.3   139.9 1426.97   150.4 1423.38
   152.1 1423.19   181.9 1420.61   218.6 1419.88   225.9 1417.87   234.4 1416.91
   240.61417.875   245.7 1419.58   262.8 1419.68   271.3 1420.63   283.8  1424.3
   296.8  1427.4   316.7 1430.66   334.1 1432.31   348.6 1435.21   357.6 1435.86
     362 1436.91     371 1441.03   375.5 1442.43   388.9 1442.91   397.6 1445.33
#Mann= 4 ,-1,0
       0     .05       0      30     .07       0   225.9    .045       0
   240.6     .07       0
Bank Sta=225.9,240.6
XS Rating Curve= 0 ,0
Exp/Cntr(USF)=0,0
Exp/Cntr=0.3,0.1

Type RM Length L Ch R = 1 ,852     ,44.3,44.3,44.3
XS GIS Cut Line= 4
2174557.15017731694662.3822110452174547.41911299694366.027070222
2174549.18839741694290.8324822522174589.88193913694182.021490248
#Sta/Elev= 30
       0 1429.21    44.7 1426.97    69.2 1426.32   109.3 1427.16   129.3 1427.02
   137.3 1427.49   197.3 1426.29   241.3 1426.57   269.3 1425.97     313 1426.34
   317.4 1425.43   321.4  1422.6   325.4 1418.61   329.4 1416.01   333.4 1415.64
   337.4 1415.77   341.4 1416.59   345.4 1418.62   353.4 1424.79   356.7 1425.89
   369.4 1426.36   380.3 1427.56   390.6 1426.77   397.1 1427.53   424.7 1427.16
   448.8  1425.9   456.1 1426.28   471.6 1425.99   474.8 1426.47   487.9 1426.91
#Mann= 6 ,-1,0
       0     .05       0      20     .08       0     220     .07       0
   325.4    .045       0   345.4     .07       0  421.73     .06       0
Bank Sta=325.4,345.4
XS Rating Curve= 0 ,0
Exp/Cntr(USF)=0,0
Exp/Cntr=0.3,0.1

Type RM Length L Ch R = 1 ,807     ,166.7,166.7,166.7
XS GIS Cut Line= 4
2174602.72260554 694655.270383052174587.21265481694395.263326845
2174593.40515029694305.0298212812174634.98333422694182.064553894
#Sta/Elev= 30
       0  1430.7    14.1 1429.97    27.1 1428.93    46.4 1428.31   106.3 1427.71
   154.4 1427.76   178.4 1426.48   204.8 1426.26   294.6 1424.23   302.7 1423.78
   306.7 1423.22   310.7 1422.11   318.7 1417.63   319.6 1417.39   322.7 1416.25
   323.4  1416.5   326.7 1416.63   330.9 1416.01   334.7 1416.23     337 1417.42
   342.7  1420.4   346.8 1421.51   350.9 1422.01   363.4 1421.59   384.5 1420.25
   409.5 1420.31   422.8 1421.29   439.4 1423.19   452.1 1424.31   480.7 1424.72
#Mann= 6 ,-1,0
       0     .05       0      10     .08       0     210     .07       0
   319.6    .045       0     337     .07       0  410.91     .06       0
Bank Sta=319.6,337
XS Rating Curve= 0 ,0
Exp/Cntr(USF)=0,0
Exp/Cntr=0.3,0.1

Type RM Length L Ch R = 1 ,641     ,229.5,229.5,229.5
XS GIS Cut Line= 2
2174825.57736509694436.215181758 2174655.7260605694130.128976609
#Sta/Elev= 30
       0 1427.78     9.1 1426.14    12.6 1426.03    21.8 1427.03    26.3 1427.04
    40.1  1424.7    59.2 1423.88    62.9 1423.34    72.1  1419.6    76.7 1419.03
   108.7 1418.67     118 1418.92   136.1 1418.75   156.2 1418.19   200.4 1419.66
   204.8 1419.47     218 1419.65   232.7 1418.78   245.9    1420   250.4 1419.46
   256.3 1416.97   261.1 1415.84   264.2 1415.54   268.8 1415.84     271 1416.47
   277.9  1419.7   285.7 1421.27   291.7 1423.07   300.4 1425.07   350.1  1425.3
#Mann= 4 ,-1,0
       0     .07       0   261.1    .045       0   268.8     .07       0
     330     .06       0
Bank Sta=261.1,268.8
XS Rating Curve= 0 ,0
Exp/Cntr(USF)=0,0
Exp/Cntr=0.3,0.1

Type RM Length L Ch R = 1 ,411     ,205.2,205.2,205.2
XS GIS Cut Line= 2
2174957.77798194694355.4458131662174819.12518041694042.151369359
#Sta/Elev= 30
       0 1427.54     2.5 1427.44    11.2 1425.48      20 1424.74    28.7  1423.3
    41.8 1422.32    51.4 1420.98    57.5 1420.58      83 1420.62      90 1419.84
    98.7 1418.25   111.8 1417.01   151.5 1417.36   164.3 1417.87     200 1417.33
   212.4 1417.62   221.4 1417.19   241.2 1418.31   273.7 1418.46   278.1  1418.2
   286.8  1415.3   289.51415.043   295.6  1414.8   299.5 1415.03   303.1 1416.61
   308.7 1421.62   312.2 1423.97   317.4 1425.64   326.2 1425.91   342.6 1425.44
#Mann= 8 ,-1,0
       0     .06       0      10     .07       0      50      .1       0
     230     .08       0   289.5    .045       0   299.5     .08       0
     300     .07       0     330     .08       0
Bank Sta=289.5,299.5
XS Rating Curve= 0 ,0
Exp/Cntr(USF)=0,0
Exp/Cntr=0.3,0.1

Type RM Length L Ch R = 1 ,206     ,46.3,46.3,46.3
XS GIS Cut Line= 6
2174974.96539075694352.5446251022174933.75601416694257.833998384
2174993.76434737694132.1937675722175000.03281592694082.046019147
2175045.51057869693988.0136400832174999.39436079693891.496183401
#Sta/Elev= 30
       0 1427.36     4.7 1427.54    25.5  1423.3    50.3 1421.39    64.7 1419.68
    92.8 1421.06   103.3 1419.75   129.6 1418.73   179.4 1417.86   192.6 1418.07
   232.6 1420.15     237 1420.04   241.4 1419.15   254.5 1415.11   257.7  1414.3
   265.7 1413.94   273.8 1414.38     276 1415.08   284.7  1418.6   289.9 1419.67
   351.8 1419.44   369.6 1418.79   391.8 1419.49   418.4 1419.52   437.7 1417.46
   466.6 1417.34   471.6 1417.88   484.6 1421.74   493.6 1423.71   504.5 1424.37
#Mann= 9 ,-1,0
       0     .06       0      10     .07       0     100      .1       0
   254.5    .045       0     276      .1       0  323.06     .06       0
  383.06      .1       0  427.51     .06       0  437.51      .1       0
Bank Sta=254.5,276
XS Rating Curve= 0 ,0
Exp/Cntr(USF)=0,0
Exp/Cntr=0.3,0.1

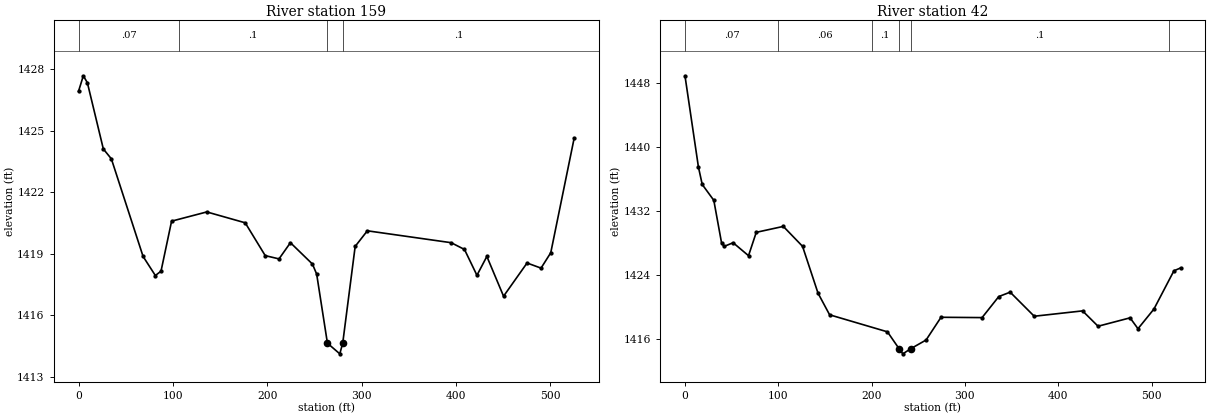
Type RM Length L Ch R = 1 ,159     ,117.6,117.6,117.6
XS GIS Cut Line= 6
2174990.82358435694350.0037026642174958.90727687694259.123806729
  2175038.688372694125.9252990192175047.04633007694083.613136286
2175086.13954154693991.4961226132175031.08495181693873.387274244
#Sta/Elev= 30
       0 1426.93     5.1 1427.69     9.4 1427.35    26.3 1424.12    34.8 1423.64
    68.4 1418.88    81.4 1417.95    87.4 1418.16    98.6  1420.6   135.9 1421.05
   176.6 1420.52   197.8 1418.92   212.4 1418.76   224.5 1419.55   247.8 1418.51
   252.3 1418.02   263.7 1414.65   276.8 1414.13   279.9 1414.65   293.1 1419.37
     306 1420.13   394.8 1419.55   408.9 1419.22   422.1 1417.96   432.6 1418.88
   450.3 1416.94   475.2 1418.56     490 1418.31   500.3 1419.06   525.1 1424.65
#Mann= 4 ,-1,0
       0     .07       0  106.32      .1       0   263.7    .045       0
   279.9      .1       0
Bank Sta=263.7,279.9
XS Rating Curve= 0 ,0
Exp/Cntr(USF)=0,0
Exp/Cntr=0.3,0.1

Type RM Length L Ch R = 1 ,42      ,,,
XS GIS Cut Line= 4
2175213.52372639694347.0951724942175145.39693611694087.161481246
2175128.06010413694008.9611145572175063.19656386693838.459251923
#Sta/Elev= 30
       0 1448.93    14.4 1437.53    18.5 1435.34    30.9 1433.36    39.2 1428.04
      42  1427.6    51.6 1428.06    68.1 1426.44    76.4 1429.36   105.4  1430.1
     126 1427.61   142.6 1421.75     155 1419.05     217 1416.92   229.4 1414.82
   233.5 1414.17   241.8  1414.8   258.4  1415.9   274.4 1418.74   318.4  1418.7
   336.3 1421.33   348.5 1421.88   374.3 1418.87   426.1 1419.54   442.7 1417.62
     477 1418.67   485.5 1417.31   502.6 1419.77     524 1424.55   531.2 1424.91
#Mann= 6 ,-1,0
       0     .07       0     100     .06       0     200      .1       0
   229.4    .045       0   241.8      .1       0  518.81     .07       0
Bank Sta=229.4,241.8
XS Rating Curve= 0 ,0
Exp/Cntr(USF)=0,0
Exp/Cntr=0.3,0.1
LCMann Table=0

Chan Stop Cuts=-1
Use User Specified Reach Order=0
Composite Channel Slope=5